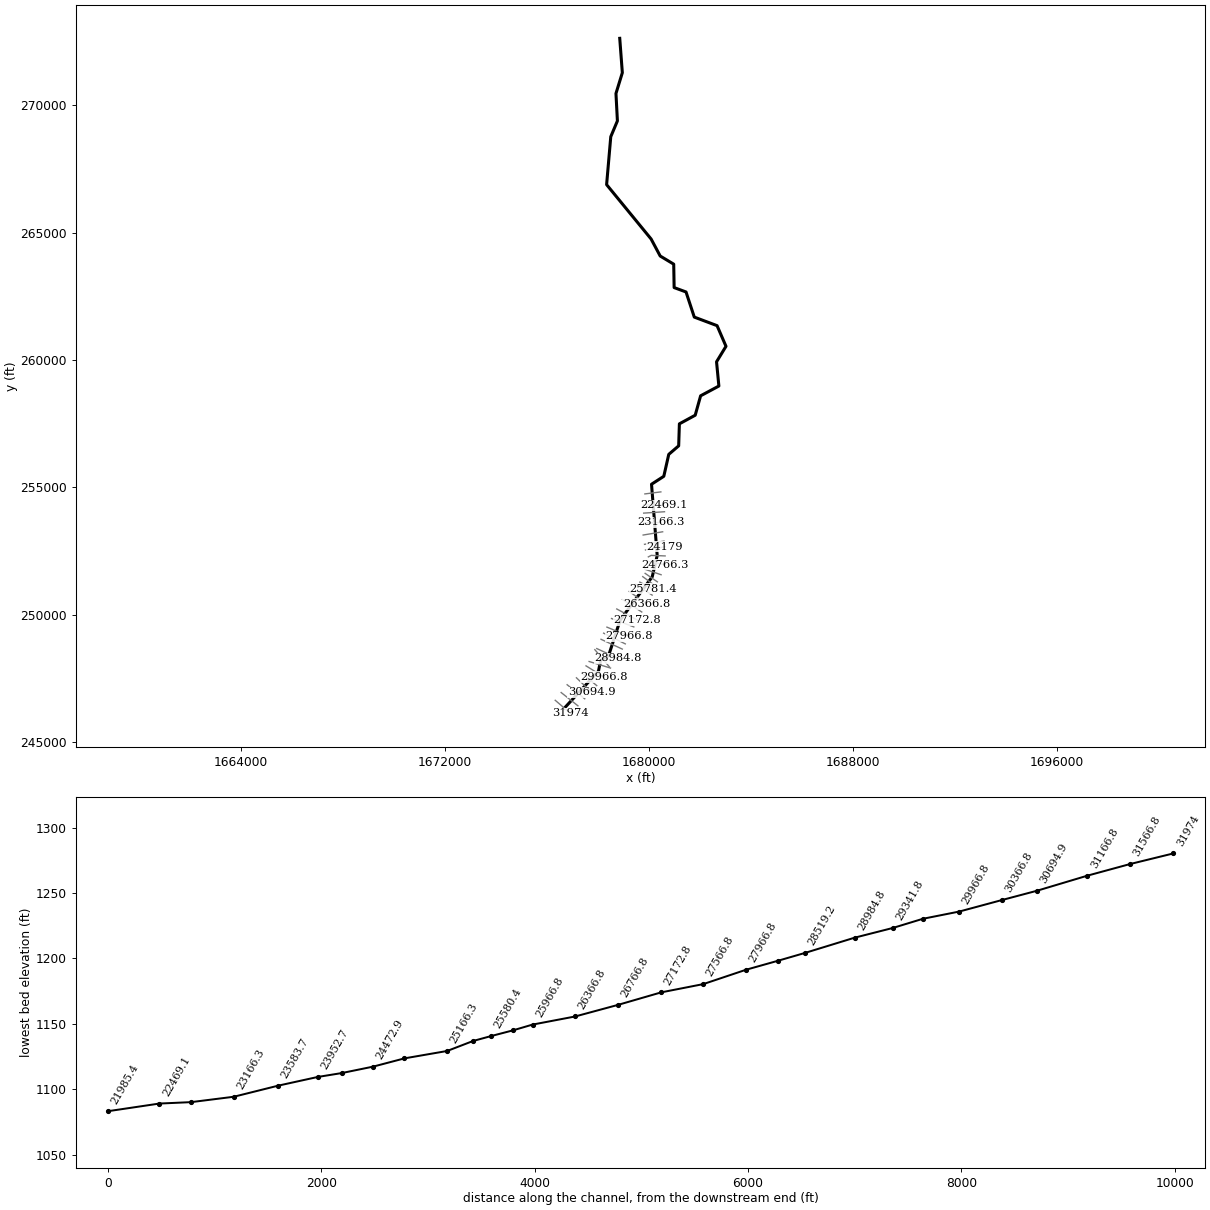
--- ISLANDCRK.prj (project) ---

Proj Title=ISLANDCRK
Current Plan=p01
Default Exp/Contr=0,0
English Units
Geom File=g01
Flow File=f01
Plan File=p01
BEGIN DESCRIPTION:
END DESCRIPTION:
DSS Export Rating Curves= 0
DSS Export Rating Curve Sorted= 0
DSS Export Volume Flow Curves= 0
DXF OffsetX= 0
DXF OffsetY= 0
DXF ScaleX= 0
DXF ScaleY= 0

--- ISLANDCRK.p01 (plan) ---

Plan Title=Floodplain
Program Version=4.00
Geom File=g01
Flow File=f01
K Sum by GR=0
Std Step Tol=0.01
Critical Tol=0.01
Num of Std Step Trials=20
Max Error Tol=0.3
Flow Tol Ratio=0.001
Split Flow NTrial=30
Split Flow Tol=0.02
Split Flow Ratio=0.02
Log Output Level=0
Friction Slope Method=1
Unsteady Friction Slope Method=2
Unsteady Bridges Friction Slope Method=1
Global Log Level=0
CheckData=False
Run HTab=0
Run UNet=0
Run PostProcess=0
UNET Theta=0
UNET Theta Warmup=0
UNET ZTol=0
UNET ZSATol=0
UNET MxIter=0
UNET MaxInSteps=0
UNET DtIC=0
UNET DtMin=0
UNET MaxCRTS=0
UNET WFStab=0
UNET SFStab=0
UNET WFX=0
UNET SFX=0
UNET DSS MLevel=0
UNET DZMax Abort=0
UNET Convert EG Bridges=0
UNET Use Existing IB Tables=0
UNET Froude Limit=0
UNET Froude Power=0
Write IC File=0
Echo Input=False
Echo Output=False
Write Detailed=0

--- ISLANDCRK.f01 (steady flow) ---

Flow Title=NFF Regression Equation
Program Version=4.00
Number of Profiles=1
Profile Names=P100yr
River Rch & RM=ISLANDCRK,Main      ,31974
906.5707
River Rch & RM=ISLANDCRK,Main      ,31166.8
936.0025
River Rch & RM=ISLANDCRK,Main      ,28519.2
1016.146
River Rch & RM=ISLANDCRK,Main      ,25409.3
1087.914
River Rch & RM=ISLANDCRK,Main      ,25166.3
1258.159
River Rch & RM=ISLANDCRK,Main      ,23952.7
1268.264
River Rch & RM=ISLANDCRK,Main      ,23583.7
2049.573
River Rch & RM=ISLANDCRK,Main      ,16827.6
2204.702
River Rch & RM=ISLANDCRK,Main      ,14009.4
2395.672
River Rch & RM=ISLANDCRK,Main      ,13562.1
2805.562
River Rch & RM=ISLANDCRK,Main      ,6887.5
3505.255
River Rch & RM=ISLANDCRK,Main      ,6887.5
2954.798
River Rch & RM=ISLANDCRK,Main      ,182.7
3657.873
Boundary for River Rch & Prof#=ISLANDCRK,Main      ,1
Up Type=0
Dn Type=3
Dn Slope=0.00752

--- ISLANDCRK.g01 (geometry) ---

Geom Title=USGS 10m DEM
Program Version=4.10

River Reach=ISLANDCRK       ,Main
Reach XY= 30
     1676683.091       246330.06     1678021.974      247783.605
     1678107.681      248209.824     1678421.554      248398.611
     1678874.411      249791.929      1680132.22      251491.013
     1680326.798      252326.078     1680104.423      255124.296
     1680586.235      255435.853     1680780.814      256297.556
      1681169.97      256632.277     1681197.767      257496.296
     1681818.564      257834.492     1682030.987       258597.19
     1682747.442      258981.113     1682655.945      259931.997
      1683026.57      260541.212     1682676.792      261351.955
     1681782.659      261687.834     1681458.362      262674.623
     1680991.607      262847.195     1680975.392      263766.808
     1680444.935      264086.472     1680088.208      264754.755
     1678341.638      266889.324     1678504.944      268771.404
      1678765.54      269392.201     1678708.788      270469.329
      1678958.96      271284.704     1678857.038      272635.169

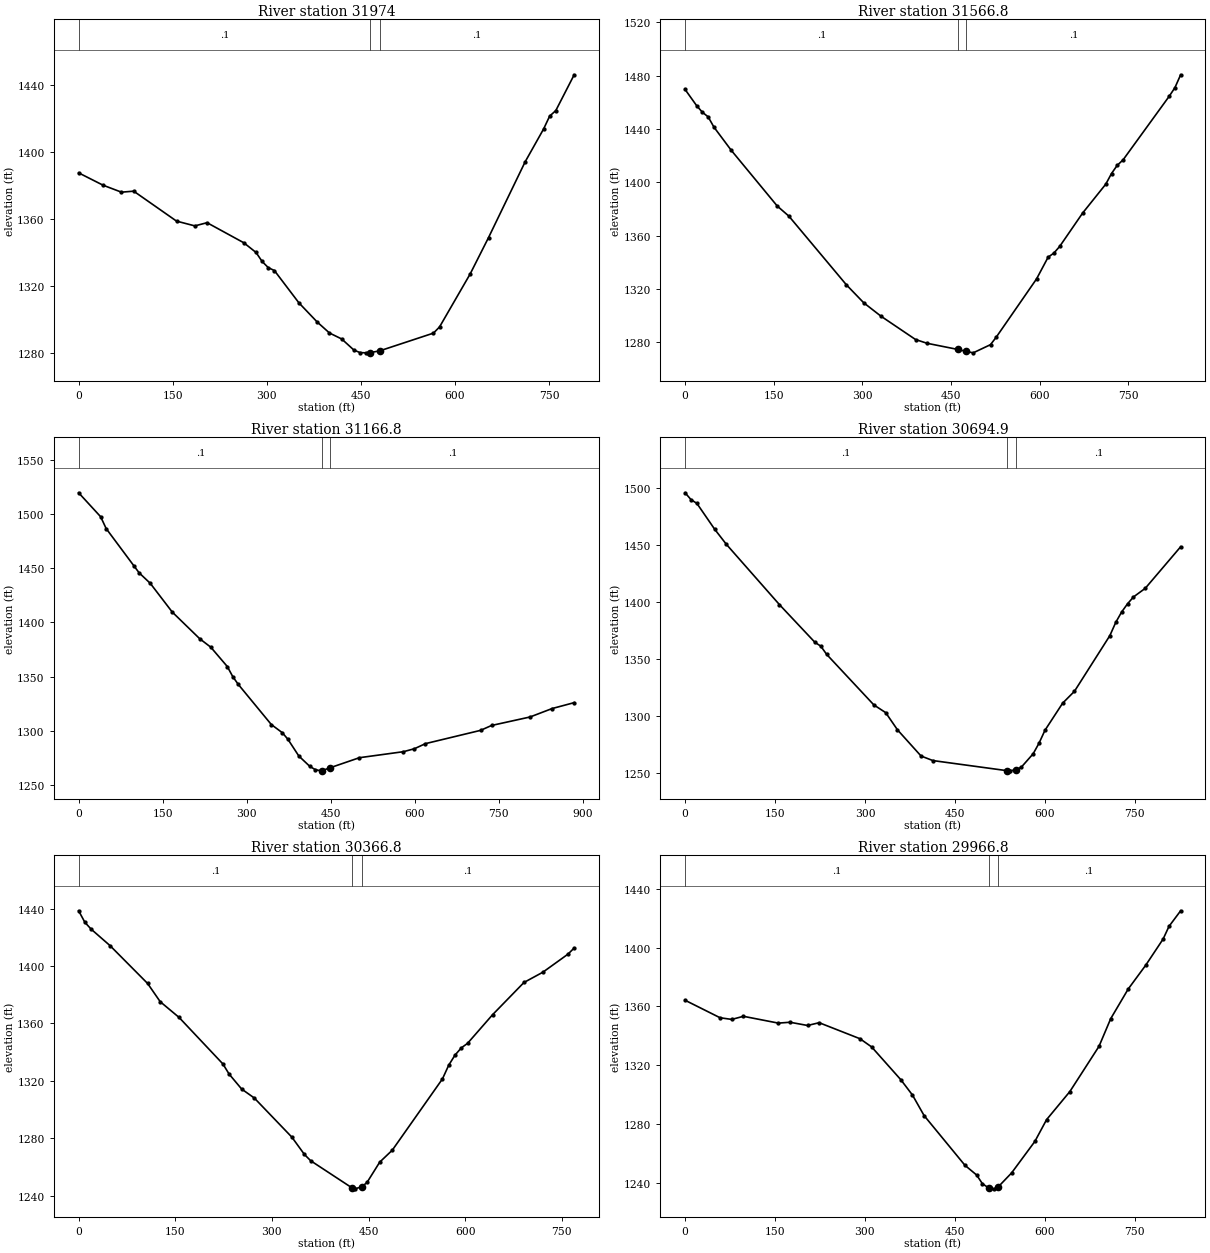
Type RM Length L Ch R = 1 ,31974   ,406.1,407.3,408.5
XS GIS Cut Line= 2
     1676325.072      246640.257      1676925.08      246126.133
#Sta/Elev= 30
       0 1387.68      39 1380.31    68.3 1376.16    87.8 1376.76   156.1  1358.9
   185.3 1356.05   204.8 1357.95   263.4 1345.98   282.9  1340.2   292.6 1334.84
   302.4 1331.16   312.2  1329.4   351.2 1310.17   380.4 1298.73     400 1292.16
   419.5  1288.6     439 1281.97   448.7 1280.48   458.5 1280.33   465.3 1280.48
   480.3 1281.54   565.8 1292.09   575.5 1295.77   624.3 1327.35   653.6 1349.05
   712.1 1394.32   741.4 1413.82   751.1 1421.52   760.9 1424.83   790.2 1446.18
#Mann= 3 , 0 , 0
       0      .1       0   465.3    .045       0   480.3      .1       0
Bank Sta=465.3,480.3
XS Rating Curve= 0 ,0
Exp/Cntr=0.3,0.1

Type RM Length L Ch R = 1 ,31566.8 ,399.9,399.6,399.3
XS GIS Cut Line= 2
     1676558.101      246944.379     1677216.018      246424.167
#Sta/Elev= 30
       0  1469.7    19.5 1457.59    29.3 1452.61      39 1449.19    48.8 1441.48
      78 1424.15     156 1382.27   175.6 1374.73   273.1 1323.14   302.3 1309.73
   331.6 1299.64   390.1 1282.15   409.6 1279.34   461.2 1274.76   476.2 1273.21
   487.6 1272.18   516.9 1278.32   526.6 1283.94   594.9 1327.67   614.4 1343.92
   624.2 1347.02   633.9 1351.94   672.9 1377.07     712 1398.69   721.7 1406.67
   731.4 1412.83   741.2 1416.87   819.2 1464.52     829 1471.04   838.7 1480.73
#Mann= 3 , 0 , 0
       0      .1       0   461.2    .045       0   476.2      .1       0
Bank Sta=461.2,476.2
XS Rating Curve= 0 ,0
Exp/Cntr=0.3,0.1

Type RM Length L Ch R = 1 ,31166.8 ,473.8,471.8,469.9
XS GIS Cut Line= 2
     1676793.163      247251.155     1677483.889      246698.571
#Sta/Elev= 30
       0 1519.45    39.3 1497.38    49.1 1486.52    98.3 1452.39   108.1 1445.66
   127.8 1436.08   167.1 1409.59   216.2 1384.97   235.9 1377.21   265.4 1359.38
   275.2 1350.05     285 1342.92     344 1305.93   363.6 1298.43   373.5 1292.44
   393.1 1276.94   412.8 1267.35   422.6 1264.38   432.4  1263.3   434.6 1263.48
   449.6 1266.26   501.2  1275.4   579.9 1280.95   599.5 1283.69   619.2 1288.37
   717.5 1300.59   737.1 1305.09   805.9 1312.92   845.2 1320.68   884.6 1326.12
#Mann= 3 , 0 , 0
       0      .1       0   434.6    .045       0   449.6      .1       0
Bank Sta=434.6,449.6
XS Rating Curve= 0 ,0
Exp/Cntr=0.3,0.1

Type RM Length L Ch R = 1 ,30694.9 ,326.8,328.1,329.5
XS GIS Cut Line= 2
     1677157.383      247523.179     1677755.344      246952.441
#Sta/Elev= 30
       0 1495.98     9.8 1490.01    19.7 1486.63    49.2 1464.05    68.9 1450.67
   157.4 1397.74   216.5 1364.67   226.3 1361.29   236.2 1354.02   314.9 1309.66
   334.6  1302.9   354.3 1287.77   393.6 1264.79   413.3  1260.8   537.6 1251.88
   541.2 1251.78   552.6  1252.8   560.9 1255.03   580.6 1266.77   590.4 1276.09
   600.3 1287.41   629.8 1311.23   649.5 1321.65   708.5  1370.5   718.4 1382.18
   728.2  1391.3     738 1398.45   747.9 1404.48   767.6 1412.08   826.6 1448.55
#Mann= 3 , 0 , 0
       0      .1       0   537.6    .045       0   552.6      .1       0
Bank Sta=537.6,552.6
XS Rating Curve= 0 ,0
Exp/Cntr=0.3,0.1

Type RM Length L Ch R = 1 ,30366.8 ,396.7,400.1,403.4
XS GIS Cut Line= 2
     1677367.083      247713.964     1677953.869      247216.767
#Sta/Elev= 30
       0 1438.59     9.7 1430.53    19.5 1425.74    48.7  1414.3   107.1 1387.88
   126.6 1375.19   155.8 1364.25   223.9 1331.79   233.6 1324.68   253.1 1314.24
   272.6 1308.04     331  1280.7   350.5 1268.63   360.2 1264.26   424.8 1245.21
   428.4 1244.68   439.8 1246.12   447.8 1249.29   467.3  1263.3   486.8 1271.64
   564.7 1321.37   574.4 1330.91   584.1  1337.9   593.9 1342.97   603.6 1346.13
   642.5 1366.13   691.2  1388.6   720.4 1395.72   759.4 1408.31   769.1 1412.62
#Mann= 3 , 0 , 0
       0      .1       0   424.8    .045       0   439.8      .1       0
Bank Sta=424.8,439.8
XS Rating Curve= 0 ,0
Exp/Cntr=0.3,0.1

Type RM Length L Ch R = 1 ,29966.8 ,335,340.9,346.7
XS GIS Cut Line= 2
     1677533.891      247991.976     1678236.079      247555.419
#Sta/Elev= 30
       0 1364.12    58.4 1352.22    77.8  1351.1    97.3 1353.21   155.6 1348.58
   175.1 1349.17   204.3 1346.97   223.7 1348.86   291.8 1337.96   311.3 1332.36
   359.9  1310.1   379.4 1299.64   398.8 1285.67   466.9 1251.89   486.4 1245.28
   496.1 1239.33   506.6 1236.47   515.6 1235.87   521.6 1236.85   544.7 1246.66
   583.6 1268.13   603.1 1282.91     642 1302.05   690.6 1332.79   710.1 1351.58
   739.3 1371.76   768.5 1387.93   797.6 1405.78   807.4  1414.4   826.8 1424.98
#Mann= 3 , 0 , 0
       0      .1       0   506.6    .045       0   521.6      .1       0
Bank Sta=506.6,521.6
XS Rating Curve= 0 ,0
Exp/Cntr=0.3,0.1

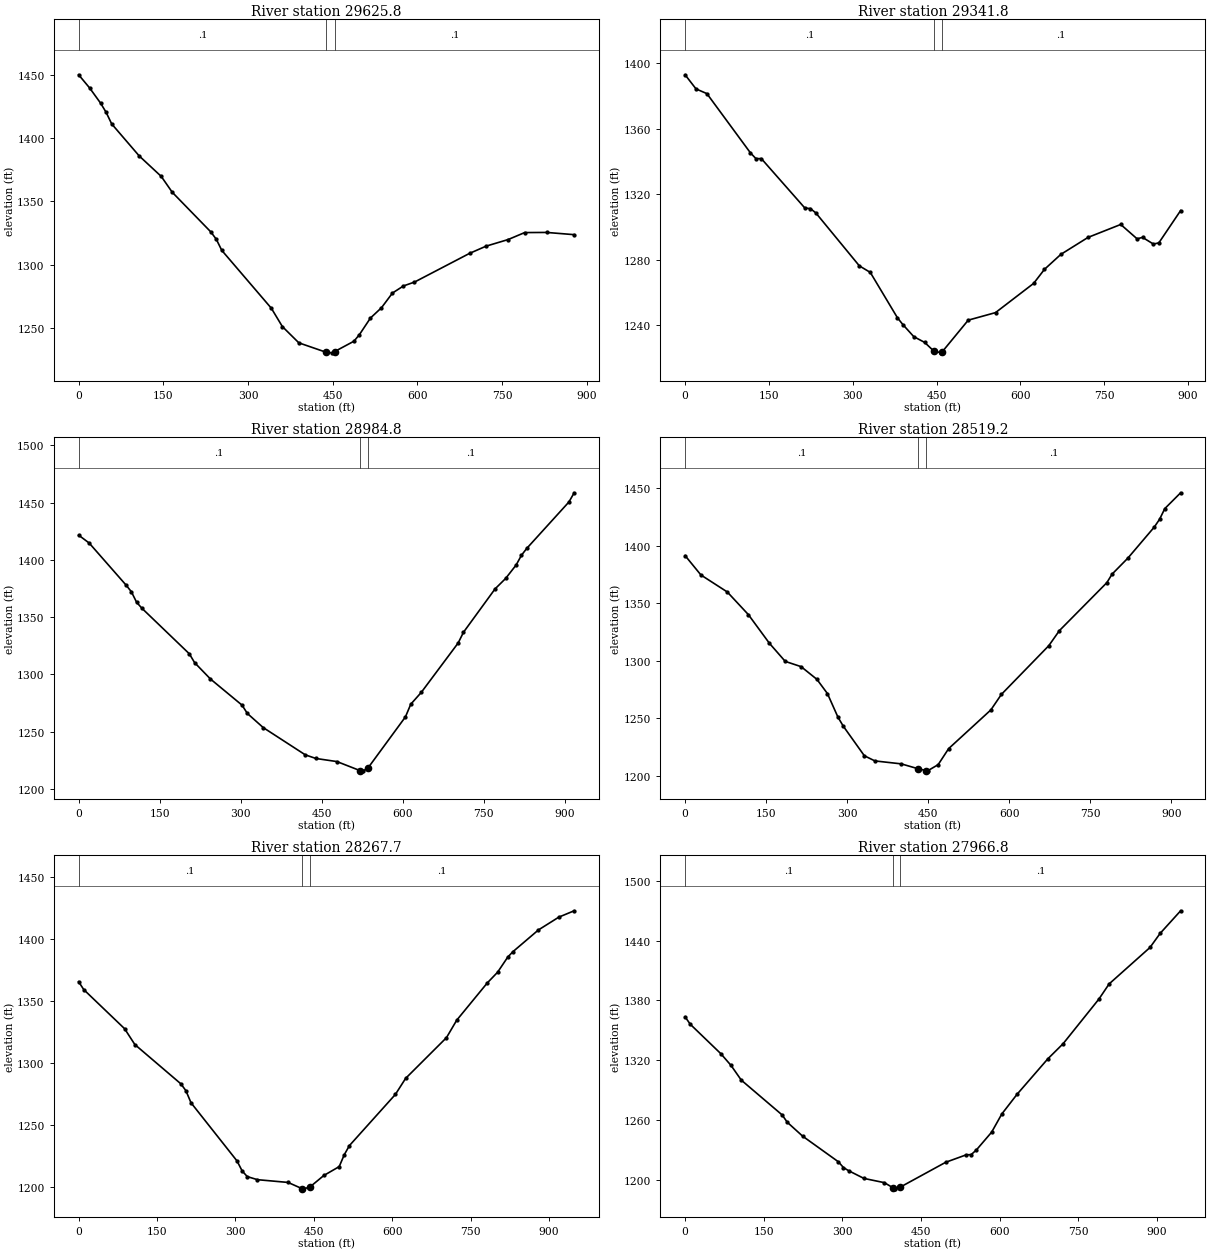
Type RM Length L Ch R = 1 ,29625.8 ,296.4,283.5,270.6
XS GIS Cut Line= 2
     1677655.417      248163.306     1678494.452      247905.946
#Sta/Elev= 30
       0 1450.13    19.5  1439.7      39 1427.64    48.8 1420.36    58.5 1411.32
   107.3 1385.97   146.3  1369.8   165.8 1357.26     234 1325.98   243.8 1320.12
   253.5 1311.35   341.3 1265.58   360.8 1251.11     390 1238.24   438.2 1230.82
   448.6 1230.34   453.2  1231.3   487.6 1239.54   497.3 1244.74   516.8 1257.85
   536.3 1265.97   555.8 1277.61   575.3 1283.23   594.8 1286.27   692.3 1308.95
   721.6 1314.67   760.6 1319.88   789.9  1325.4   828.9 1325.51   877.6 1323.75
#Mann= 3 , 0 , 0
       0      .1       0   438.2    .045       0   453.2      .1       0
Bank Sta=438.2,453.2
XS Rating Curve= 0 ,0
Exp/Cntr=0.3,0.1

Type RM Length L Ch R = 1 ,29341.8 ,346.7,356.8,366.8
XS GIS Cut Line= 2
     1677879.738      248627.862     1678451.611      247950.335
#Sta/Elev= 30
       0 1392.99    19.5 1384.38      39 1381.49   116.9 1345.33   126.7 1341.83
   136.4 1341.83   214.4 1311.61   224.1 1311.34   233.8 1308.72   311.8 1276.35
   331.3 1272.39     380 1244.63   389.7  1240.5   409.2 1233.15   428.7 1229.63
   444.6 1224.48   457.9 1223.28   459.6 1223.74   506.6 1243.23   555.4 1247.83
   623.6 1265.67     643 1274.25   672.3 1283.38     721 1293.75   779.4 1301.63
   808.7 1292.87   818.4 1293.75   837.9 1289.67   847.6  1290.4   886.6 1310.13
#Mann= 3 , 0 , 0
       0      .1       0   444.6    .045       0   459.6      .1       0
Bank Sta=444.6,459.6
XS Rating Curve= 0 ,0
Exp/Cntr=0.3,0.1

Type RM Length L Ch R = 1 ,28984.8 ,465.6,465.6,465.5
XS GIS Cut Line= 2
     1677956.434      248671.247     1678789.768      248287.829
#Sta/Elev= 30
       0 1421.57    19.5 1414.68    87.8 1377.98    97.6 1372.18   107.3 1362.99
   117.1 1357.77   204.9 1318.01   214.7 1310.29     244 1296.02   302.5 1273.19
   312.3 1265.96   341.6 1253.65   419.6 1229.82   439.1 1226.67   478.2 1223.95
   520.8 1216.09     527 1215.87   535.8 1218.47     605 1262.98   614.8    1274
   634.3 1284.35   702.6 1327.48   712.4 1336.81   770.9 1374.68   790.4 1383.75
     810 1395.59   819.7 1403.99   829.5 1409.98   907.6 1450.52   917.3 1458.54
#Mann= 3 , 0 , 0
       0      .1       0   520.8    .045       0   535.8      .1       0
Bank Sta=520.8,535.8
XS Rating Curve= 0 ,0
Exp/Cntr=0.3,0.1

Type RM Length L Ch R = 1 ,28519.2 ,252.4,251.7,251
XS GIS Cut Line= 2
     1678123.627      249034.629      1678956.96      248651.211
#Sta/Elev= 30
       0 1391.43    29.3 1374.57    78.1 1359.79   117.1 1340.11   156.1 1315.14
   185.4  1299.4   214.7 1294.84     244  1283.8   263.5  1271.4     283 1250.84
   292.8 1243.06   331.8 1217.33   351.3 1212.83   400.1 1210.27   431.7 1205.96
   446.7 1204.36   448.9  1204.2   468.4 1209.56   487.9 1223.55     566  1257.2
   585.5 1270.69   673.3  1313.1   692.9 1326.19   780.7 1367.89   790.4 1375.32
   819.7 1389.28   868.5 1416.25   878.3 1423.02     888 1432.32   917.3 1446.08
#Mann= 3 , 0 , 0
       0      .1       0   431.7    .045       0   446.7      .1       0
Bank Sta=431.7,446.7
XS Rating Curve= 0 ,0
Exp/Cntr=0.3,0.1

Type RM Length L Ch R = 1 ,28267.7 ,299.2,300.8,302.3
XS GIS Cut Line= 2
     1678225.234      249276.119     1679075.018      248854.935
#Sta/Elev= 30
       0  1365.6     9.8 1359.22      88 1327.61   107.6 1314.82   195.6 1283.11
   205.3 1277.56   215.1 1267.78   303.1  1220.8   312.9 1212.76   322.7 1208.15
   342.2 1205.65   400.9 1203.42   427.2 1198.47   430.2 1198.25   442.2 1199.59
   469.3 1209.04   498.7 1216.21   508.4  1225.8   518.2 1233.16   606.2 1274.51
   625.8 1287.48     704  1320.4   723.6 1334.49   782.2 1364.64   801.8 1373.23
   821.3 1385.48   831.1 1389.82     880 1407.42   919.1 1417.78   948.4  1422.9
#Mann= 3 , 0 , 0
       0      .1       0   427.2    .045       0   442.2      .1       0
Bank Sta=427.2,442.2
XS Rating Curve= 0 ,0
Exp/Cntr=0.3,0.1

Type RM Length L Ch R = 1 ,27966.8 ,399.2,399.9,400.7
XS GIS Cut Line= 2
     1678353.976      249513.231     1679228.073      249152.994
#Sta/Elev= 30
       0 1363.64     9.8 1356.23    68.2  1326.7    87.7 1314.91   107.2 1300.23
   185.2 1265.34   194.9 1258.05   224.2 1244.12   292.4 1218.45   302.1 1212.68
   311.9 1209.52   341.1  1201.8   380.1 1197.53   395.8 1192.68   399.6 1191.34
   410.8 1193.15   497.1 1217.92   536.1 1225.36   545.8 1225.64   555.6 1230.21
   584.8 1248.09   604.3 1266.37   633.5 1286.16     692 1321.55   721.2 1336.72
   789.5 1381.43     809 1396.61   886.9 1433.08   906.4 1447.28   945.4 1469.86
#Mann= 3 , 0 , 0
       0      .1       0   395.8    .045       0   410.8      .1       0
Bank Sta=395.8,410.8
XS Rating Curve= 0 ,0
Exp/Cntr=0.3,0.1

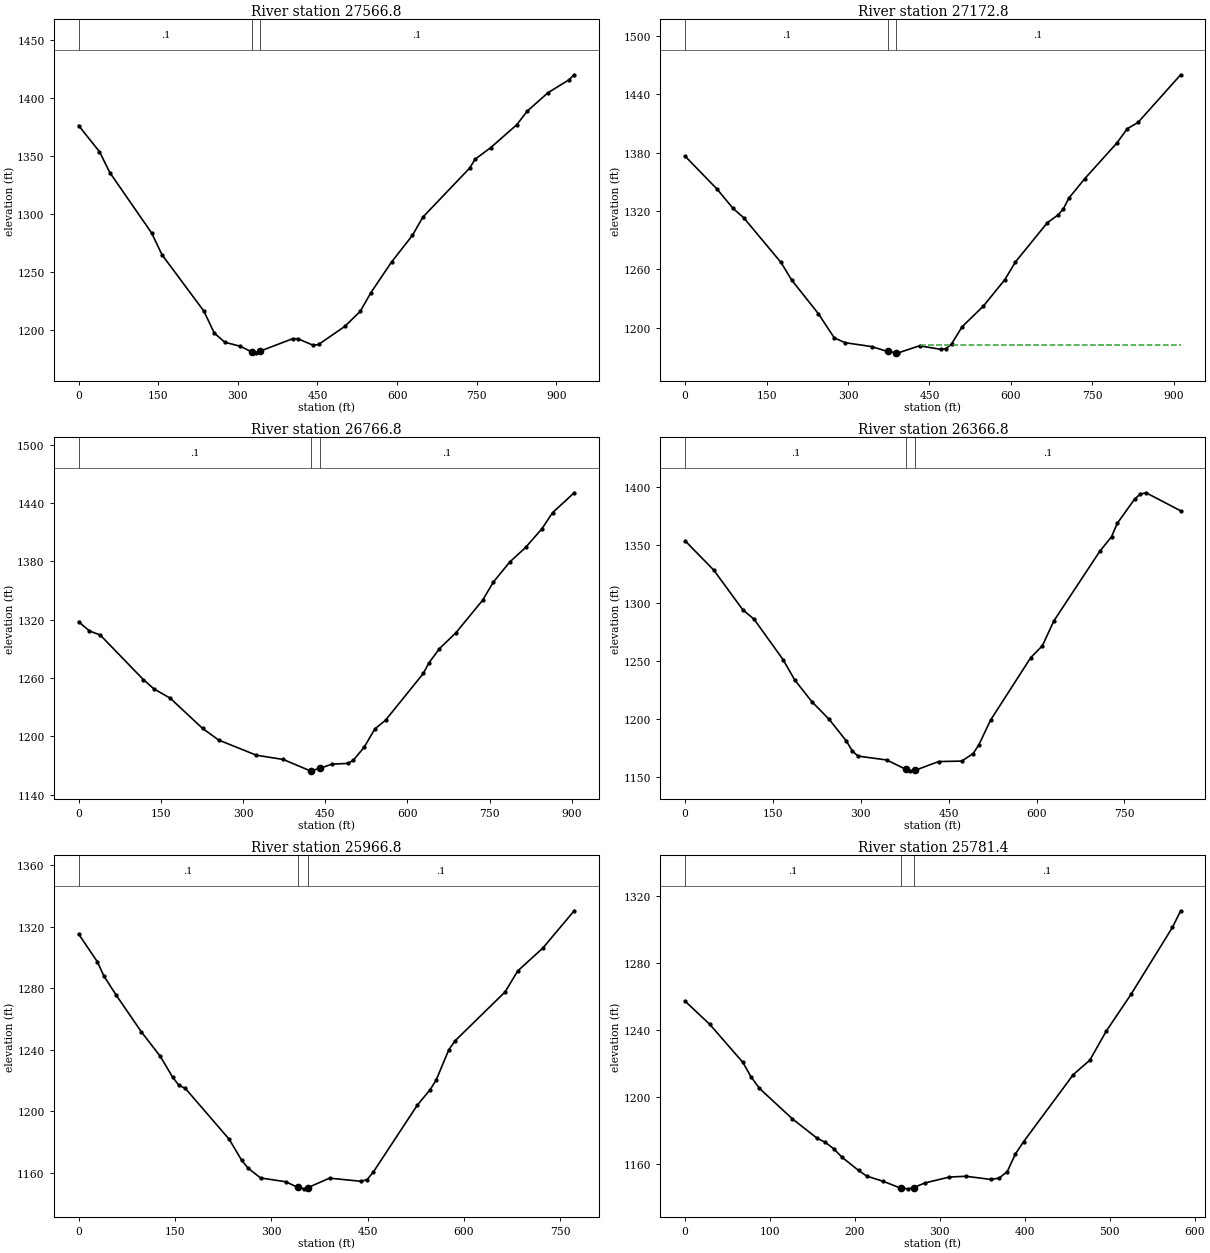
Type RM Length L Ch R = 1 ,27566.8 ,396.5,393.9,391.4
XS GIS Cut Line= 2
     1678535.822      249850.793     1679409.648      249521.909
#Sta/Elev= 30
       0 1376.25    39.3 1353.71      59 1335.57   137.6 1283.62   157.2 1264.82
   235.9 1216.39   255.5 1197.49   275.2 1189.55   304.7    1186   327.4  1180.9
   334.2 1180.38   342.4 1181.92     403  1192.5   412.8 1192.57   442.3 1186.86
   452.1 1187.58   501.2 1203.08   530.7 1216.14   550.4 1232.06   589.7 1258.69
     629 1281.66   648.6 1297.33   737.1 1339.75   746.9 1347.19   776.4 1357.22
   825.6 1376.97   845.2 1388.66   884.5  1404.6   923.8 1415.63   933.7    1420
#Mann= 3 , 0 , 0
       0      .1       0   327.4    .045       0   342.4      .1       0
Bank Sta=327.4,342.4
XS Rating Curve= 0 ,0
Exp/Cntr=0.3,0.1

Type RM Length L Ch R = 1 ,27172.8 ,408.1,406,403.6
XS GIS Cut Line= 2
      1678739.86      250226.333     1679543.386      249793.632
#Sta/Elev= 30
       0 1376.23    58.9 1342.39    88.3 1322.54   107.9    1313   176.6 1267.01
   196.3 1248.89   245.3 1214.44   274.8 1189.42   294.4 1184.53   343.5 1180.51
   372.9 1175.46   387.9 1174.22   392.5 1174.07   431.8 1181.31     471 1177.65
   480.8 1178.46   490.7 1183.24   510.3 1200.97   549.5 1222.25   588.8 1249.28
   608.4 1267.54   667.3 1307.95   686.9 1315.84   696.7 1322.16   706.6 1333.02
     736 1353.13   794.9 1389.62   814.5 1404.56   834.1  1410.9   912.6 1459.94
#Mann= 3 , 0 , 0
       0      .1       0   372.9    .045       0   387.9      .1       0
#XS Ineff= 2 , 0
                          434.01         1181.73
Permanent Ineff=
       F       F
Bank Sta=372.9,387.9
XS Rating Curve= 0 ,0
Exp/Cntr=0.3,0.1

Type RM Length L Ch R = 1 ,26766.8 ,401,400,398.9
XS GIS Cut Line= 2
     1678961.598      250598.536     1679720.849      250107.392
#Sta/Elev= 30
       0 1317.93    19.7 1308.38    39.3 1304.32     118 1258.41   137.6 1248.75
   167.1 1239.24   226.1 1208.19   255.6 1196.15   324.4 1180.54   373.5 1176.16
   422.6 1164.47   424.8 1164.65   439.8 1166.96     462 1171.34   491.4 1172.11
   501.3  1175.4   520.9 1188.68   540.6 1207.64   560.2 1216.67     629  1264.7
   638.9 1275.28   658.5 1290.29     688 1306.26   737.2 1340.02   756.8 1358.71
   786.3 1379.13   815.8 1394.46   845.3 1413.52   864.9 1430.19   904.3 1450.64
#Mann= 3 , 0 , 0
       0      .1       0   424.8    .045       0   439.8      .1       0
Bank Sta=424.8,439.8
XS Rating Curve= 0 ,0
Exp/Cntr=0.3,0.1

Type RM Length L Ch R = 1 ,26366.8 ,399.3,399.8,400.3
XS GIS Cut Line= 2
      1679226.79      250915.058     1679914.576      250422.198
#Sta/Elev= 30
       0 1353.86    49.2 1328.46    98.4 1294.47   118.1 1286.09   167.3 1251.46
   186.9 1234.16   216.5 1215.21     246 1200.02   275.5 1181.22   285.3 1172.86
   295.2 1168.36   344.4 1164.97   377.6  1156.8   383.7 1155.64   392.6 1156.08
   432.9 1163.64   472.3 1164.03   491.9 1170.57   501.8 1178.28   521.5 1199.28
   590.3  1253.3     610 1263.41   629.7 1284.89   708.4  1345.1   728.1  1357.3
   737.9  1368.9   767.4 1389.73   777.3 1394.14   787.1 1395.24   846.1 1379.72
#Mann= 3 , 0 , 0
       0      .1       0   377.6    .045       0   392.6      .1       0
Bank Sta=377.6,392.6
XS Rating Curve= 0 ,0
Exp/Cntr=0.3,0.1

Type RM Length L Ch R = 1 ,25966.8 ,182.7,185.4,188.1
XS GIS Cut Line= 2
     1679487.985      251199.907     1680128.644      250770.059
#Sta/Elev= 30
       0  1315.2    29.3 1297.06    39.1 1288.04    58.6 1275.38    97.7 1251.53
     127  1235.7   146.5 1221.97   156.2 1216.75     166 1214.81   234.4 1181.68
   253.9 1167.94   263.7 1162.95   283.2  1156.5   322.3 1154.04   341.5 1150.32
   351.6 1149.42   356.5 1150.12   390.6 1156.37   439.5 1154.34   449.2 1155.43
     459 1160.47   527.4 1203.94   546.9 1213.75   556.6 1220.16   576.2  1239.8
     586  1245.7   664.1 1277.62   683.6 1291.19   722.7 1306.06   771.5 1330.33
#Mann= 3 , 0 , 0
       0      .1       0   341.5    .045       0   356.5      .1       0
Bank Sta=341.5,356.5
XS Rating Curve= 0 ,0
Exp/Cntr=0.3,0.1

Type RM Length L Ch R = 1 ,25781.4 ,204.5,200.7,197
XS GIS Cut Line= 2
     1679644.776      251279.826     1680164.671       251014.89
#Sta/Elev= 30
       0 1257.21    29.2 1243.27    68.1 1220.55    77.8 1211.78    87.5 1205.09
   126.4  1186.8   155.6 1175.17   165.3 1172.74     175 1168.93   184.8 1163.86
   204.2 1155.99     214 1152.56   233.4 1149.44     254 1145.37   262.6 1144.97
     269 1145.66     282 1148.44   311.2 1152.02   330.6 1152.49   359.8 1150.61
   369.6 1151.34   379.3 1155.24     389 1165.88   398.7 1173.23   457.1  1213.3
   476.5 1221.88     496 1239.37   525.2  1261.4   573.8 1301.31   583.5 1311.27
#Mann= 3 , 0 , 0
       0      .1       0     254    .045       0     269      .1       0
Bank Sta=254,269
XS Rating Curve= 0 ,0
Exp/Cntr=0.3,0.1

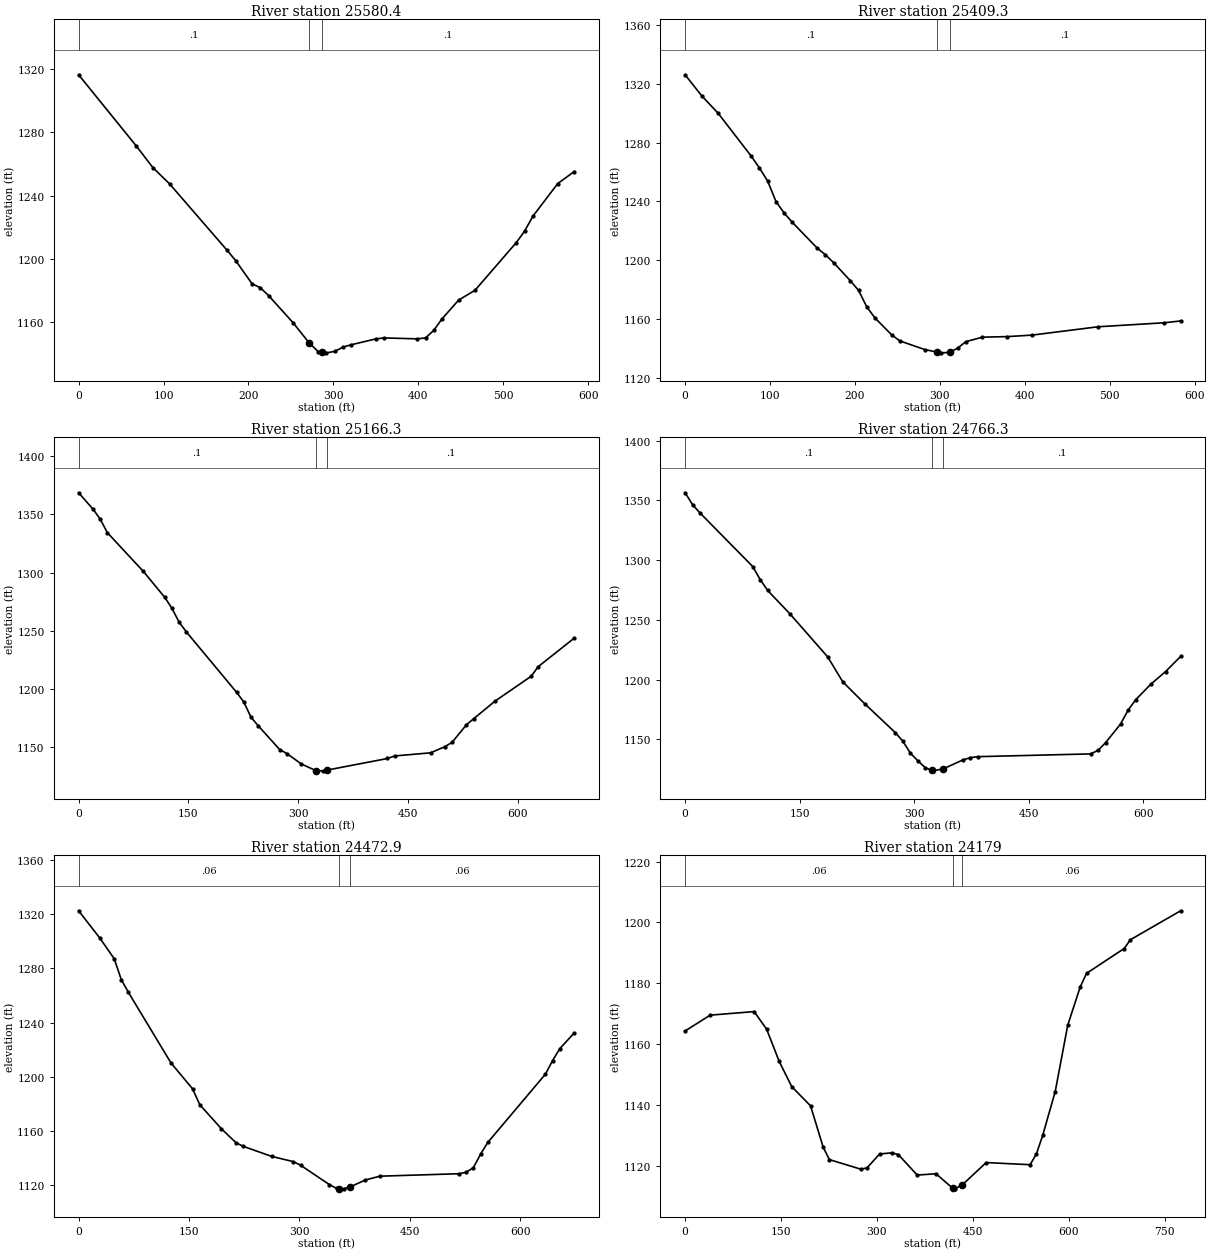
Type RM Length L Ch R = 1 ,25580.4 ,170.3,171,171.6
XS GIS Cut Line= 2
     1679759.859      251495.722     1680229.144      251148.946
#Sta/Elev= 30
       0 1316.38    68.1 1271.26    87.5 1257.68     107 1247.52     175 1205.38
   184.8 1199.04   204.2 1184.34     214 1181.81   223.7 1176.88   252.8 1159.55
   271.21147.133     282  1141.5   286.21141.158   291.8  1140.7   301.5  1141.6
   311.2  1144.3   320.9  1145.8   350.1 1149.52   359.8 1150.12   398.7 1149.54
   408.5 1150.14   418.2 1154.92   427.9 1162.17   447.4    1174   466.8 1180.26
   515.4  1210.4   525.2 1217.64   534.9 1227.04   564.1  1247.6   583.5 1255.23
#Mann= 3 , 0 , 0
       0      .1       0   271.2    .045       0   286.2      .1       0
Bank Sta=271.2,286.2
XS Rating Curve= 0 ,0
Exp/Cntr=0.3,0.1

Type RM Length L Ch R = 1 ,25409.3 ,236.8,243,249.2
XS GIS Cut Line= 2
     1679854.073      251624.171     1680333.594      251291.694
#Sta/Elev= 30
       0 1326.21    19.4 1312.01    38.9 1300.01    77.8 1270.87    87.5 1262.78
    97.2 1253.87     107 1239.92   116.7 1232.02   126.4 1225.64   155.6 1208.18
   165.3 1203.66     175 1198.21   194.5 1186.03   204.2 1179.46     214 1168.08
   223.7 1160.58   243.1 1149.23   252.8 1145.03     282 1139.15   296.7  1137.4
   301.5 1136.89   311.7 1137.18   320.9 1140.11   330.6 1144.51   350.1 1147.56
   379.3 1147.94   408.5 1148.96   486.3 1154.64   564.1 1157.36   583.5  1158.6
#Mann= 3 , 0 , 0
       0      .1       0   296.7    .045       0   311.7      .1       0
Bank Sta=296.7,311.7
XS Rating Curve= 0 ,0
Exp/Cntr=0.3,0.1

Type RM Length L Ch R = 1 ,25166.3 ,396.7,399.9,403.2
XS GIS Cut Line= 2
     1679839.323      251788.439     1680480.634      251570.265
#Sta/Elev= 30
       0 1368.66    19.6 1354.62    29.4 1346.06    39.3 1334.29    88.4 1301.02
   117.8 1278.57   127.6 1269.13   137.4 1257.22   147.3 1248.86     216 1196.82
   225.8 1188.53   235.6 1175.43   245.4 1168.14   274.9 1147.52   284.7 1144.15
   304.3 1135.22   324.4 1129.42   333.8 1129.25   339.4 1129.87   422.2 1139.88
     432 1142.06   481.1 1144.76   500.7 1150.05   510.5 1153.78   530.1 1168.89
     540 1174.13   569.4 1189.36   618.5 1210.62   628.3 1218.98   677.4 1243.47
#Mann= 3 , 0 , 0
       0      .1       0   324.4    .045       0   339.4      .1       0
Bank Sta=324.4,339.4
XS Rating Curve= 0 ,0
Exp/Cntr=0.3,0.1

Type RM Length L Ch R = 1 ,24766.3 ,289.8,293.2,296.5
XS GIS Cut Line= 2
     1680000.632      252089.144     1680638.136      251969.112
#Sta/Elev= 30
       0 1356.35     9.8 1346.39    19.7 1339.34    88.5 1294.64    98.3  1283.7
   108.1 1274.58   137.6 1254.74   186.8 1218.87   206.4  1198.1   235.9 1179.29
   275.2  1155.6     285 1148.44   294.9 1138.44   304.7 1131.96   314.5 1126.21
   322.9    1124   324.4  1123.6   337.9 1125.25   363.7 1132.75   373.5 1134.66
   383.3 1135.47   530.8 1137.78   540.6 1140.76   550.4 1147.17   570.1  1162.8
   579.9 1174.42   589.7    1183   609.4 1195.97     629 1206.72   648.7 1219.36
#Mann= 3 , 0 , 0
       0      .1       0   322.9    .045       0   337.9      .1       0
Bank Sta=322.9,337.9
XS Rating Curve= 0 ,0
Exp/Cntr=0.3,0.1

Type RM Length L Ch R = 1 ,24472.9 ,289.3,293.9,298.5
XS GIS Cut Line= 3
     1679979.712      252271.911     1680090.747      252330.374
     1680637.937        252309.3
#Sta/Elev= 30
       0 1322.55      29 1302.26    48.3 1287.19    57.9 1271.81    67.6 1262.34
   125.5 1210.18   154.8 1191.09   164.6 1179.37   193.9 1161.65   213.5 1151.47
   223.3 1148.72   262.4  1141.2   291.7 1137.37   301.5  1134.7   340.6 1120.43
   350.4 1117.62   354.2 1117.49   360.2 1117.29   369.2 1118.85   389.5 1123.82
   409.1 1126.63   516.6 1128.44   526.4 1129.52   536.2 1132.93     546 1142.92
   555.7 1151.51     634 1201.92   643.8 1211.97   653.5 1220.73   673.1 1232.32
#Mann= 3 , 0 , 0
       0     .06       0   354.2    .045       0   369.2     .06       0
Bank Sta=354.2,369.2
XS Rating Curve= 0 ,0
Exp/Cntr=0.3,0.1

Type RM Length L Ch R = 1 ,24179   ,226.2,226.2,226.2
XS GIS Cut Line= 2
     1679868.089      252542.295     1680632.754      252669.916
#Sta/Elev= 30
       0 1164.29    39.2  1169.5     108 1170.67   127.6 1164.85   147.2 1154.28
   166.8    1146   196.3 1139.65   215.9 1126.14   225.7 1121.99   274.8 1118.84
   284.6 1119.26   304.2 1123.83   323.8 1124.22   333.6 1123.63   363.1  1116.9
   392.5 1117.33   418.9 1112.52     422 1112.37   433.9 1113.74     471 1121.01
   539.7 1120.31   549.5 1123.83   559.4 1129.93     579 1144.38   598.6 1166.22
   618.2 1178.84     628 1183.25   686.9 1191.42   696.7 1194.32   775.2 1203.83
#Mann= 3 , 0 , 0
       0     .06       0   418.9    .045       0   433.9     .06       0
#XS Ineff= 2 , 0
          392.21 1117.32
Permanent Ineff=
       F       F
Bank Sta=418.9,433.9
XS Rating Curve= 0 ,0
Exp/Cntr=0.3,0.1

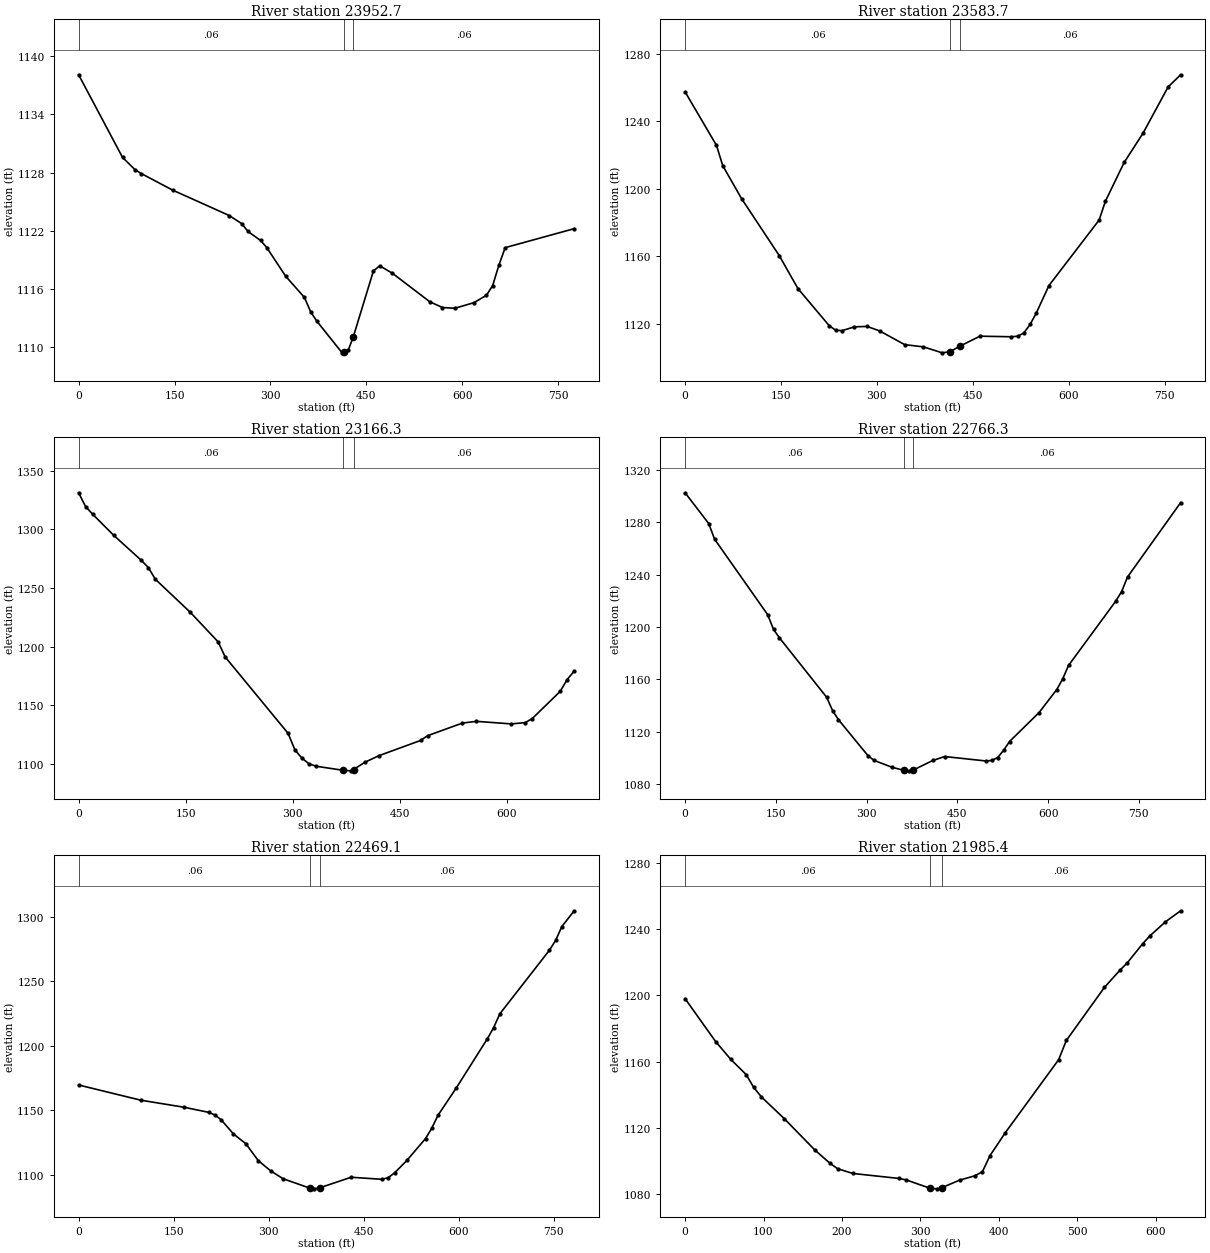
Type RM Length L Ch R = 1 ,23952.7 ,369,369,369
XS GIS Cut Line= 2
     1679830.356      252765.214     1680595.021      252892.835
#Sta/Elev= 30
       0  1138.1    68.7 1129.56    88.3 1128.29    98.1 1127.89   147.2 1126.18
   235.5 1123.56   255.1 1122.72     265 1121.91   284.6 1120.98   294.4 1120.24
   323.8 1117.29   353.3 1115.09   363.1 1113.59   372.9 1112.62   412.2 1109.37
   414.6 1109.45     422 1109.68   429.6 1111.01   461.2 1117.84     471 1118.36
   490.7  1117.6   549.5 1114.64   569.2 1114.05   588.8 1113.98   618.2 1114.55
   637.9 1115.31   647.7 1116.32   657.5 1118.45   667.3 1120.24   775.2  1122.2
#Mann= 3 , 0 , 0
       0     .06       0   414.6    .045       0   429.6     .06       0
#XS Ineff= 2 , 0
                          471.21         1118.35
Permanent Ineff=
       F       F
Bank Sta=414.6,429.6
XS Rating Curve= 0 ,0
Exp/Cntr=0.3,0.1

Type RM Length L Ch R = 1 ,23583.7 ,420.4,417.4,414.4
XS GIS Cut Line= 2
     1679776.287      253129.837     1680540.952      253257.458
#Sta/Elev= 30
       0 1257.56    49.1 1225.82    58.9 1213.78    88.3 1194.25   147.2 1160.48
   176.6 1140.83   225.7 1118.75   235.5  1116.2   245.3  1115.9     265 1118.17
   284.6 1118.42   304.2 1115.78   343.5 1107.62   372.9 1106.29   402.3 1102.75
   414.8 1103.47   429.8  1106.7   461.2 1112.63   510.3 1112.29   520.1 1112.61
   529.9 1114.54   539.7 1119.57   549.5 1126.45   569.2 1142.68   647.7 1181.52
   657.5 1192.68   686.9 1215.73   716.4 1233.06   755.6 1260.49   775.2  1267.7
#Mann= 3 , 0 , 0
       0     .06       0   414.8    .045       0   429.8     .06       0
Bank Sta=414.8,429.8
XS Rating Curve= 0 ,0
Exp/Cntr=0.3,0.1

Type RM Length L Ch R = 1 ,23166.3 ,399.2,399.9,400.7
XS GIS Cut Line= 2
     1679788.172      253602.445      1680482.37      253625.171
#Sta/Elev= 30
       0 1331.04     9.8 1319.25    19.6 1312.82    48.9 1294.97      88 1273.42
    97.8 1267.28   107.6 1257.36   156.5 1229.26   195.6 1204.04   205.4 1191.24
   293.5 1126.25   303.3 1111.94     313 1105.08   322.8 1100.29   332.6 1098.18
   370.3 1094.76   381.5 1094.24   385.3 1095.31   401.1 1101.51   420.7  1107.1
   479.4 1120.13   489.1 1124.15     538 1134.94   557.6 1136.39   606.5 1134.21
   626.1  1135.3   635.9 1138.81     675  1161.9   684.8 1172.02   694.6 1179.15
#Mann= 3 , 0 , 0
       0     .06       0   370.3    .045       0   385.3     .06       0
Bank Sta=370.3,385.3
XS Rating Curve= 0 ,0
Exp/Cntr=0.3,0.1

Type RM Length L Ch R = 1 ,22766.3 ,298.7,297.1,295.6
XS GIS Cut Line= 2
      1679796.33      253990.467     1680613.543      254044.281
#Sta/Elev= 30
       0 1302.59      39 1279.11    48.8 1267.08   136.5 1209.42   146.2 1198.15
     156 1191.71     234 1146.32   243.7 1136.19   253.5  1129.2   302.2 1101.74
     312 1098.17   341.2 1092.99   361.9 1090.43   370.5 1090.13   376.9 1090.72
   409.5 1098.05     429 1101.06   497.2 1097.67     507 1098.07   516.7 1100.32
   526.5 1105.88   536.2 1112.53     585 1134.65   614.2  1152.2     624 1160.28
   633.7 1170.65   711.7 1219.76   721.5 1227.13   731.2 1238.24     819 1295.08
#Mann= 3 , 0 , 0
       0     .06       0   361.9    .045       0   376.9     .06       0
#XS Ineff= 2 , 0
                          429.58          1100.8
Permanent Ineff=
       F       F
Bank Sta=361.9,376.9
XS Rating Curve= 0 ,0
Exp/Cntr=0.3,0.1

Type RM Length L Ch R = 1 ,22469.1 ,480.6,483.6,486.6
XS GIS Cut Line= 2
     1679793.344      254315.883     1680575.548       254296.87
#Sta/Elev= 30
       0 1169.54    97.8 1157.79   166.3  1152.3   205.4 1148.34   215.2 1146.27
     225  1142.6   244.5 1131.57   264.1 1123.96   283.6 1110.93   303.2 1102.96
   322.8  1096.9   365.7 1089.45   371.7 1089.04   380.7 1089.85   430.3 1098.02
   479.2 1096.42     489  1097.8   498.8 1101.37   518.4 1111.15   547.7 1128.02
   557.5 1135.96   567.3 1145.98   596.6  1167.5   645.5  1205.5   655.3 1214.08
   665.1 1224.76   743.3    1274   753.1 1281.58   762.9 1292.33   782.4 1304.59
#Mann= 3 , 0 , 0
       0     .06       0   365.7    .045       0   380.7     .06       0
Bank Sta=365.7,380.7
XS Rating Curve= 0 ,0
Exp/Cntr=0.3,0.1

Type RM Length L Ch R = 1 ,21985.4 ,426.1,407.7,389.3
XS GIS Cut Line= 2
     1679844.007      254744.294     1680470.908      254824.343
#Sta/Elev= 30
       0 1197.97    38.9 1172.11    58.3 1161.31    77.8 1152.19    87.5 1144.42
    97.2 1138.72   126.4 1125.59   165.3 1106.68   184.7 1098.62   194.5 1095.33
   213.9 1092.45   272.2 1089.48     282 1088.57   312.2 1083.55   320.9 1083.17
   327.2 1083.81     350 1088.41   369.5 1091.02   379.2 1093.53   388.9 1103.26
   408.4 1117.06   476.4 1161.13   486.2 1172.72   534.8 1204.76   554.2 1214.97
   563.9 1219.54   583.4 1231.03   593.1 1235.99   612.6 1244.35     632 1251.02
#Mann= 3 , 0 , 0
       0     .06       0   312.2    .045       0   327.2     .06       0
Bank Sta=312.2,327.2
XS Rating Curve= 0 ,0
Exp/Cntr=0.3,0.1