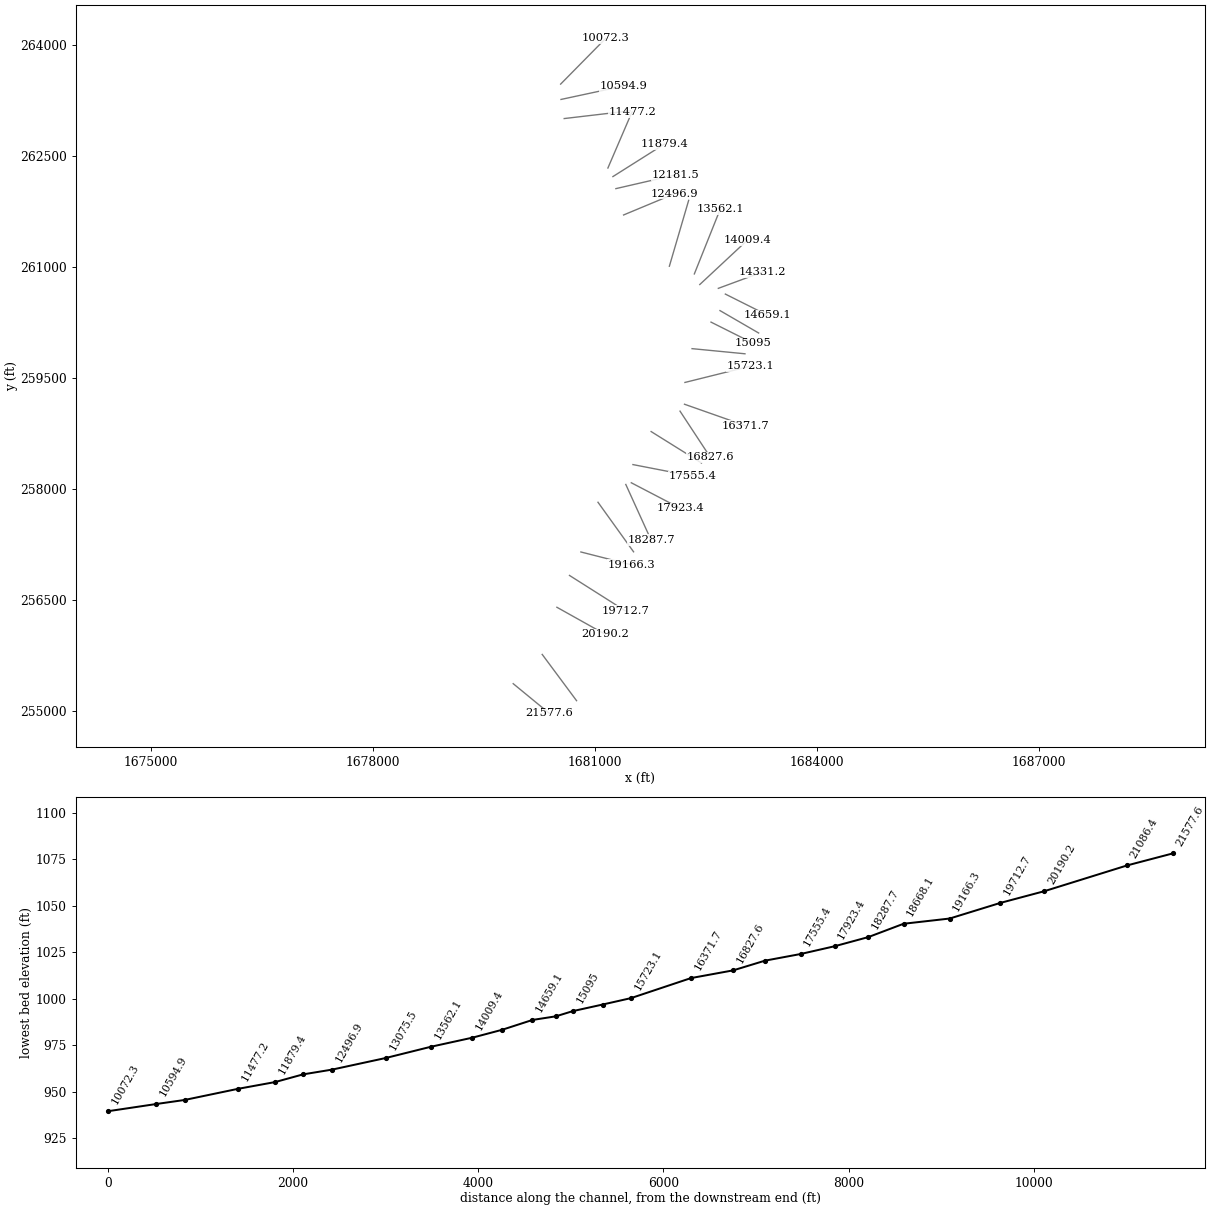
HEC-RAS study ISLANDCRK.prj: ISLANDCRK

--- ISLANDCRK.g01 (geometry) --- (continued)

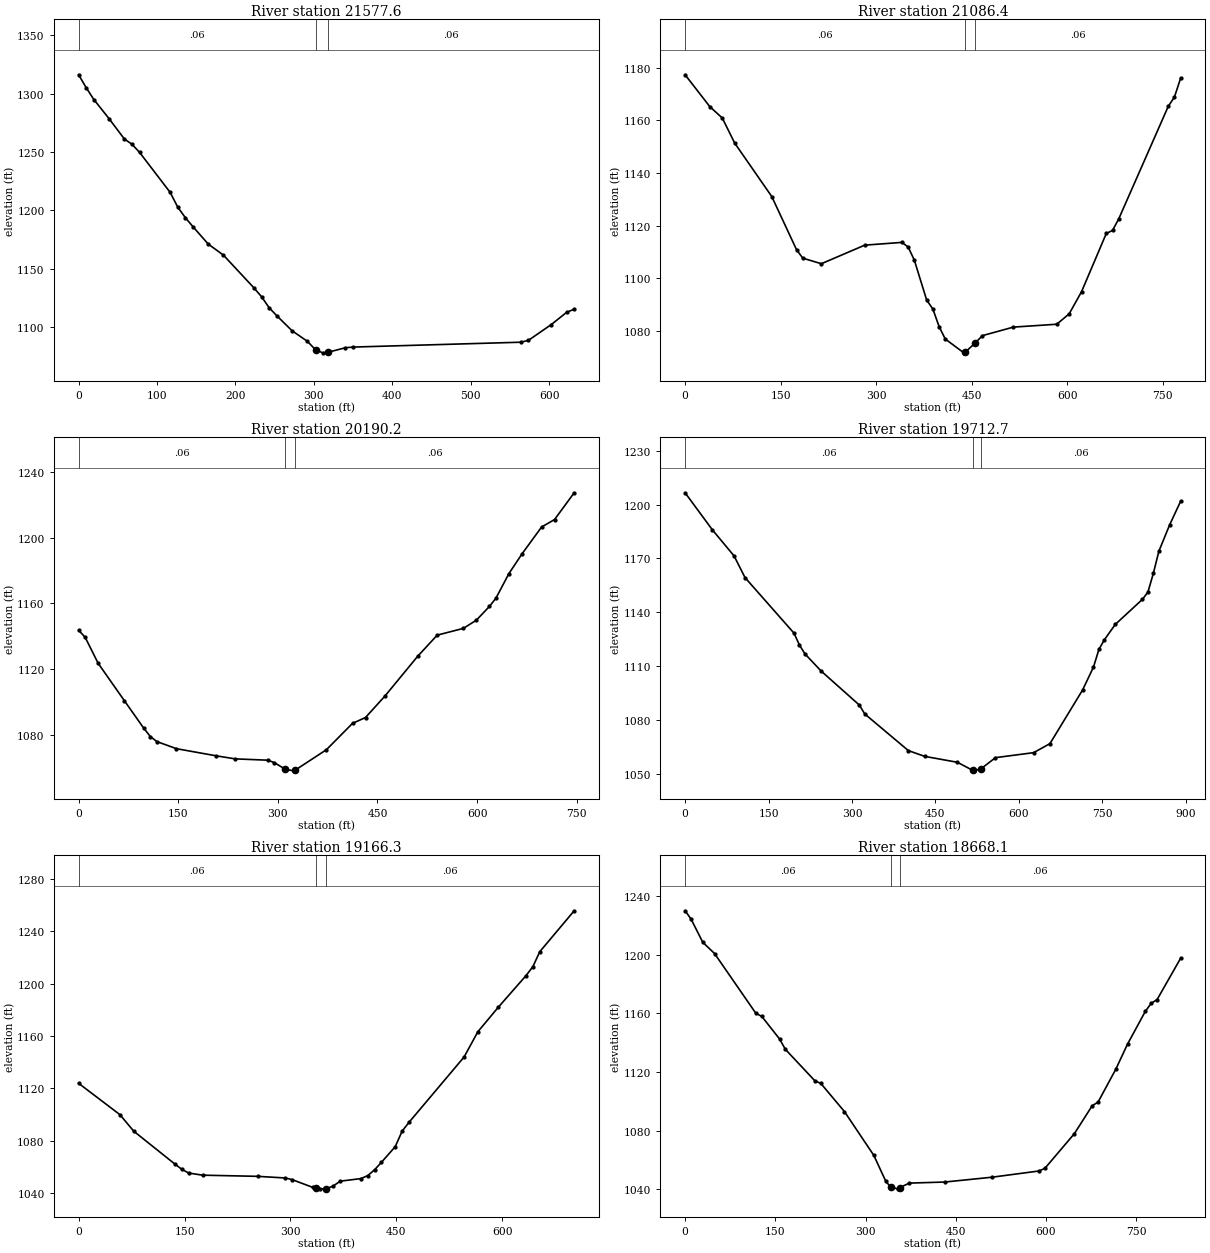
Type RM Length L Ch R = 1 ,21577.6 ,496.7,491.2,485.8
XS GIS Cut Line= 2
     1679892.946      255370.769     1680381.478      254969.833
#Sta/Elev= 30
       0 1316.05     9.7 1304.93    19.4  1294.9    38.9 1278.43    58.3 1261.14
    68.1 1256.59    77.8  1249.6   116.7 1215.48   126.4 1202.85   136.1 1193.81
   145.8 1186.11   165.3 1171.22   184.7 1161.76   223.6 1133.73   233.4 1126.09
   243.1 1116.65   252.8 1109.89   272.2 1097.06   291.7 1088.07   301.4 1081.32
   302.6 1080.93   311.1 1078.18   317.6 1078.59   340.3 1082.56     350 1083.12
   563.9 1087.27   573.6 1088.85   602.8 1102.36   622.3 1112.78     632 1115.53
#Mann= 3 , 0 , 0
       0     .06       0   302.6    .045       0   317.6     .06       0
Bank Sta=302.6,317.6
XS Rating Curve= 0 ,0
Exp/Cntr=0.3,0.1

Type RM Length L Ch R = 1 ,21086.4 ,886.1,895.7,905.2
XS GIS Cut Line= 2
     1680284.794      255765.824      1680748.81      255141.415
#Sta/Elev= 30
       0 1177.32    38.9  1165.2    58.4  1160.9    77.8 1151.41   136.1 1131.08
     175 1110.88   184.8  1107.7   213.9 1105.59     282 1112.64   340.4 1113.69
   350.1 1111.94   359.8 1106.99   379.2 1091.81     389 1088.37   398.7 1081.75
   408.4 1077.01   437.6 1071.76   440.1 1072.09   455.1 1075.43   466.8  1078.3
   515.4 1081.53   583.5 1082.62   602.9 1086.56   622.4    1095   661.2 1117.08
     671 1118.23   680.7  1122.6   758.5 1165.35   768.2 1168.88   777.9 1176.05
#Mann= 3 , 0 , 0
       0     .06       0   440.1    .045       0   455.1     .06       0
Bank Sta=440.1,455.1
XS Rating Curve= 0 ,0
Exp/Cntr=0.3,0.1

Type RM Length L Ch R = 1 ,20190.2 ,476.7,477.5,477.6
XS GIS Cut Line= 2
     1680483.235      256402.705     1681134.626      256038.713
#Sta/Elev= 30
       0 1143.61     9.8 1139.36    29.4 1123.47    68.7 1100.77    98.2 1083.81
     108 1078.82   117.8 1075.74   147.3  1071.4   206.2 1067.12   235.6 1065.19
   284.7 1064.39   294.6 1062.92   311.5 1058.79     324 1057.89   326.5 1058.42
   373.1 1070.76   412.4 1086.83     432 1090.41   461.5 1103.62   510.6 1127.78
     540 1140.65   579.3 1144.76   598.9 1149.75   618.6 1158.16   628.4 1163.19
     648 1178.22   667.6 1190.16   697.1 1206.56   716.7 1211.15   746.2 1227.46
#Mann= 3 , 0 , 0
       0     .06       0   311.5    .045       0   326.5     .06       0
Bank Sta=311.5,326.5
XS Rating Curve= 0 ,0
Exp/Cntr=0.3,0.1

Type RM Length L Ch R = 1 ,19712.7 ,541.3,546.3,552
XS GIS Cut Line= 2
     1680653.451      256832.468     1681406.191      256355.786
#Sta/Elev= 30
       0 1206.61      49 1185.97    88.1 1171.38   107.7 1159.33   195.8 1128.34
   205.6  1121.7   215.4  1116.8   244.8 1107.15   313.3 1088.24   323.1 1083.26
   401.4 1062.85   430.8 1059.63   489.6 1056.33   517.2 1051.83   518.9 1051.56
   532.2 1052.74   558.1 1058.92   626.6 1061.69     656 1066.73   714.7 1096.64
   734.3 1109.43   744.1 1119.32   753.9 1124.65   773.5 1133.21   822.4 1147.21
   832.2 1151.25     842 1161.75   851.8 1173.95   871.4 1188.86     891 1201.86
#Mann= 3 , 0 , 0
       0     .06       0   517.2    .045       0   532.2     .06       0
Bank Sta=517.2,532.2
XS Rating Curve= 0 ,0
Exp/Cntr=0.3,0.1

Type RM Length L Ch R = 1 ,19166.3 ,513.7,497.9,482.1
XS GIS Cut Line= 2
     1680807.588      257149.234      1681487.79      256976.299
#Sta/Elev= 30
       0 1123.87    58.5  1099.9      78 1087.29   136.5 1062.06   146.2  1058.1
     156 1055.25   175.5 1053.63   253.4 1052.74   292.4  1051.5   302.2 1050.26
   331.4 1044.33   335.7 1043.83   341.2 1043.18   350.7 1043.18   360.7 1045.38
   370.4 1049.04   399.7 1051.01   409.4 1053.27   419.2 1057.78   428.9  1063.5
   448.4 1075.45   458.2 1087.34   467.9 1094.04   545.9 1144.01   565.4 1163.32
   594.6 1182.22   633.6 1206.22   643.4 1213.18   653.1 1224.53   701.8 1255.82
#Mann= 3 , 0 , 0
       0     .06       0   335.7    .045       0   350.7     .06       0
Bank Sta=335.7,350.7
XS Rating Curve= 0 ,0
Exp/Cntr=0.3,0.1

Type RM Length L Ch R = 1 ,18668.1 ,384.8,380.4,376
XS GIS Cut Line= 2
     1681038.514      257820.756     1681519.339      257151.576
#Sta/Elev= 30
       0 1229.81     9.8 1224.24    29.4 1208.34      49 1200.67   117.7 1159.94
   127.5 1157.87     157  1142.5   166.8 1135.38   215.8 1113.98   225.6 1112.24
   264.9 1093.05   313.9 1063.12   333.5 1045.71   341.6 1041.64   353.2 1040.37
   356.6 1041.13   372.8 1044.28   431.6    1045   510.1 1048.28   588.6 1052.54
   598.4 1054.39   647.4 1078.02   676.9 1096.98   686.7 1099.49   716.1 1121.79
   735.7 1138.98   765.2 1161.21     775 1166.76   784.8 1169.28     824 1197.47
#Mann= 3 , 0 , 0
       0     .06       0   341.6    .045       0   356.6     .06       0
Bank Sta=341.6,356.6
XS Rating Curve= 0 ,0
Exp/Cntr=0.3,0.1

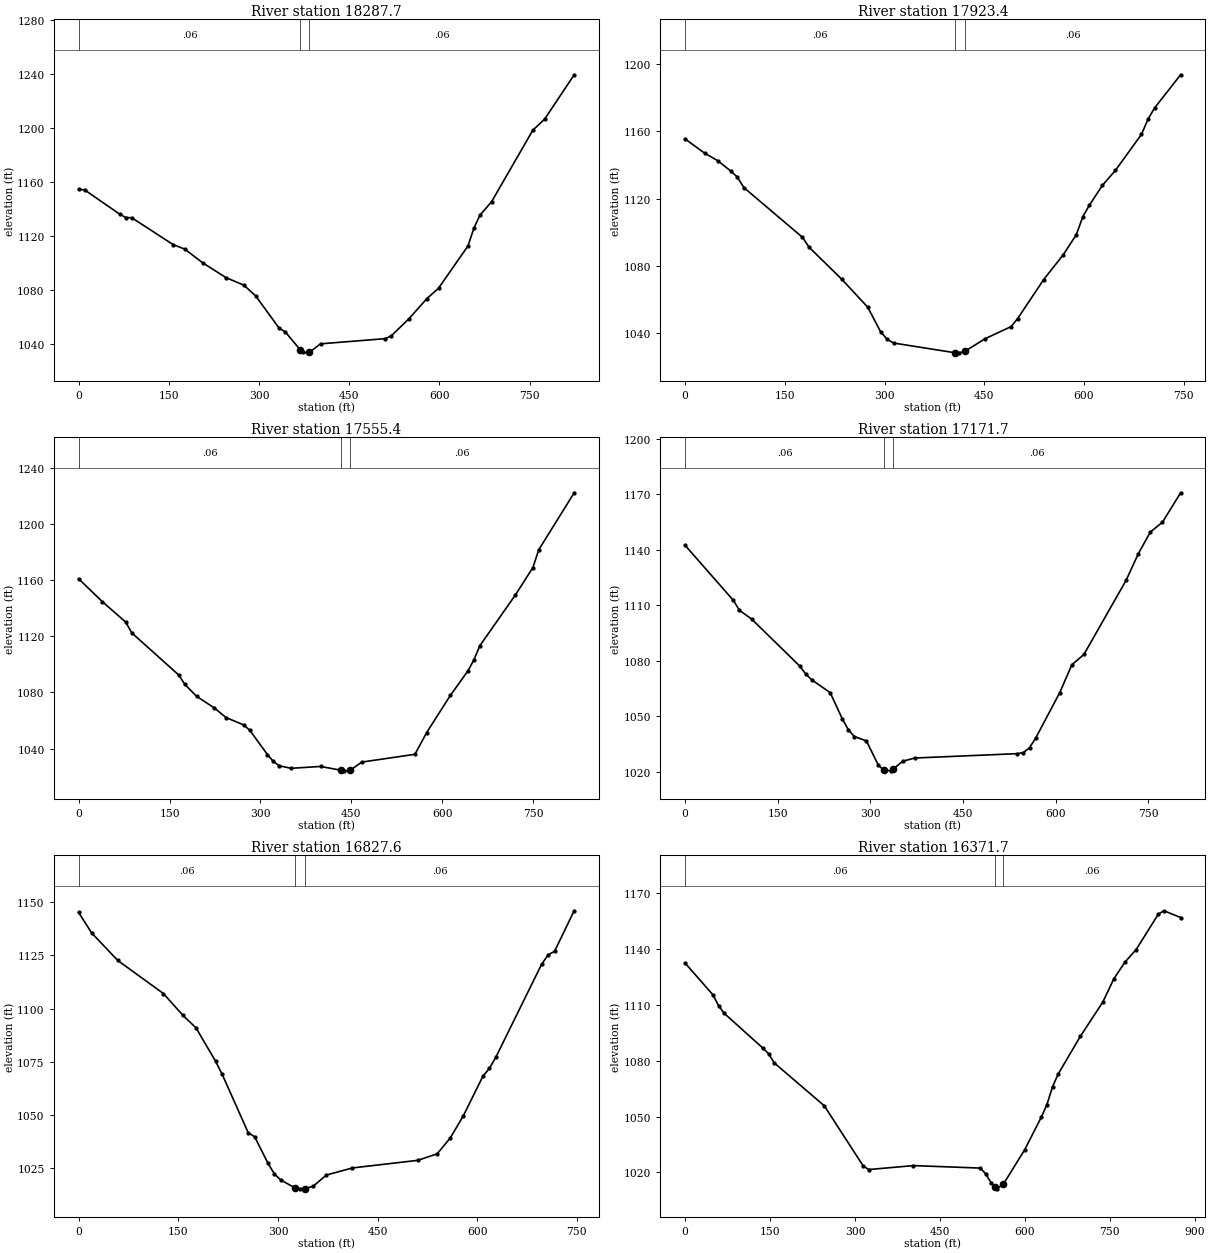
Type RM Length L Ch R = 1 ,18287.7 ,349.3,364.2,379.2
XS GIS Cut Line= 2
     1681414.557      258060.995     1681755.918      257311.018
#Sta/Elev= 30
       0 1154.44     9.8 1154.16    68.7 1135.94    78.5 1133.59    88.3 1133.44
     157 1113.56   176.6 1110.13     206 1100.08   245.2 1088.98   274.7 1083.42
   294.3  1075.5   333.5 1051.45   343.3 1048.93   368.5 1035.46   372.8 1033.51
   382.6 1033.21   383.5 1033.51   402.2 1039.89   510.1 1043.74   519.9 1045.81
   549.3 1058.52   578.8 1073.31   598.4 1081.15   647.4 1112.49   657.2 1125.63
   667.1 1135.17   686.7 1145.38   755.3 1198.39     775 1206.66     824  1239.5
#Mann= 3 , 0 , 0
       0     .06       0   368.5    .045       0   383.5     .06       0
Bank Sta=368.5,383.5
XS Rating Curve= 0 ,0
Exp/Cntr=0.3,0.1

Type RM Length L Ch R = 1 ,17923.4 ,361.6,368,374.4
XS GIS Cut Line= 2
     1681488.587      258083.935     1682149.733       257739.56
#Sta/Elev= 30
       0 1155.49    29.4 1147.02      49  1142.6    68.7 1136.38    78.5 1132.88
    88.3  1126.6   176.6 1096.98   186.4 1091.14   235.4 1072.17   274.6 1055.51
   294.3 1040.71   304.1 1036.29   313.9  1034.1   405.8 1028.36     412 1028.29
   420.8 1029.17   451.2 1036.67   490.4 1043.88   500.2 1048.63   539.5 1071.89
   568.9 1086.63   588.5 1098.49   598.3 1109.19   608.1 1116.02   627.8 1127.89
   647.4 1136.78   686.6 1158.23   696.4 1167.21   706.2 1173.88   745.5 1193.64
#Mann= 3 , 0 , 0
       0     .06       0   405.8    .045       0   420.8     .06       0
Bank Sta=405.8,420.8
XS Rating Curve= 0 ,0
Exp/Cntr=0.3,0.1

Type RM Length L Ch R = 1 ,17555.4 ,391.2,383.4,375.5
XS GIS Cut Line= 2
     1681510.915      258329.463     1682313.784      258173.634
#Sta/Elev= 30
       0 1160.83      39 1144.61    77.9 1129.93    87.6 1122.37   165.5 1092.23
   175.2 1085.69   194.7 1077.16   223.9  1068.9   243.4 1062.02   272.6 1056.76
   282.4 1053.02   311.6 1035.73   321.3  1030.8     331 1027.74   350.5 1025.91
   399.2 1027.23   432.9 1024.55   438.1 1024.11   447.9 1024.43   467.3 1030.34
     555 1035.88   574.4 1051.38   613.4 1077.75   642.6 1095.36   652.3 1103.12
   662.1 1113.17   720.5 1149.15   749.7 1168.81   759.4 1181.56   817.8 1222.08
#Mann= 3 , 0 , 0
       0     .06       0   432.9    .045       0   447.9     .06       0
Bank Sta=432.9,447.9
XS Rating Curve= 0 ,0
Exp/Cntr=0.3,0.1

Type RM Length L Ch R = 1 ,17171.7 ,354.1,344.1,334.1
XS GIS Cut Line= 2
     1681756.768      258775.388     1682437.433      258350.965
#Sta/Elev= 30
       0  1142.5    78.3 1112.69      88 1107.34   107.6 1102.68   185.9 1077.11
   195.6 1072.76   205.4 1069.66   234.8 1062.88   254.3 1048.79   264.1 1042.88
   273.9 1039.12   293.5 1036.73     313 1023.51   321.6 1020.93   332.6 1020.55
   336.6 1021.44   352.2 1025.72   371.7 1027.48     538 1029.85   547.8 1030.44
   557.6 1033.12   567.4 1038.19   606.5 1062.85   626.1 1077.93   645.6 1083.48
   714.1  1123.7   733.7 1137.99   753.2 1149.71   772.8 1155.02   802.2 1170.93
#Mann= 3 , 0 , 0
       0     .06       0   321.6    .045       0   336.6     .06       0
Bank Sta=321.6,336.6
XS Rating Curve= 0 ,0
Exp/Cntr=0.3,0.1

Type RM Length L Ch R = 1 ,16827.6 ,440.9,455.9,470.9
XS GIS Cut Line= 2
     1682147.073      259051.186     1682557.022      258428.081
#Sta/Elev= 30
       0 1145.16    19.6 1135.55    58.9 1122.62   127.6 1107.08     157 1096.83
   176.6 1090.99   206.1  1075.3   215.9 1069.22   255.2 1041.74     265 1039.77
   284.6 1027.59   294.4 1022.45   304.2 1019.49   326.3 1015.67   333.7 1015.33
   341.3 1015.41   353.3 1016.61   372.9 1021.82   412.2 1025.15   510.3 1028.71
   539.8  1031.8   559.4 1039.24     579  1049.6   608.5 1068.21   618.3 1071.93
   628.1 1077.24   696.8 1120.76   706.6 1125.22   716.4 1126.94   745.9 1145.96
#Mann= 3 , 0 , 0
       0     .06       0   326.3    .045       0   341.3     .06       0
Bank Sta=326.3,341.3
XS Rating Curve= 0 ,0
Exp/Cntr=0.3,0.1

Type RM Length L Ch R = 1 ,16371.7 ,635.3,648.3,661.2
XS GIS Cut Line= 2
     1682207.766      259144.353     1683033.499      258854.027
#Sta/Elev= 30
       0 1132.42    49.2 1115.36      59 1109.64    68.8 1105.52   137.7 1086.67
   147.5  1083.7   157.4 1078.83   245.9 1055.78   314.7 1023.42   324.5 1021.54
   403.2 1023.66   521.2 1022.33   531.1 1019.24   540.9 1014.18   547.2 1012.25
   550.7 1011.18   562.2  1013.7   599.9 1032.21   629.4  1049.8   639.2 1056.47
   649.1 1066.09   658.9 1072.78   698.3 1093.16   737.6 1111.36   757.3 1123.95
   776.9 1132.96   796.6 1139.62     836 1158.75   845.8 1160.51   875.3 1156.89
#Mann= 3 , 0 , 0
       0     .06       0   547.2    .045       0   562.2     .06       0
Bank Sta=547.2,562.2
XS Rating Curve= 0 ,0
Exp/Cntr=0.3,0.1

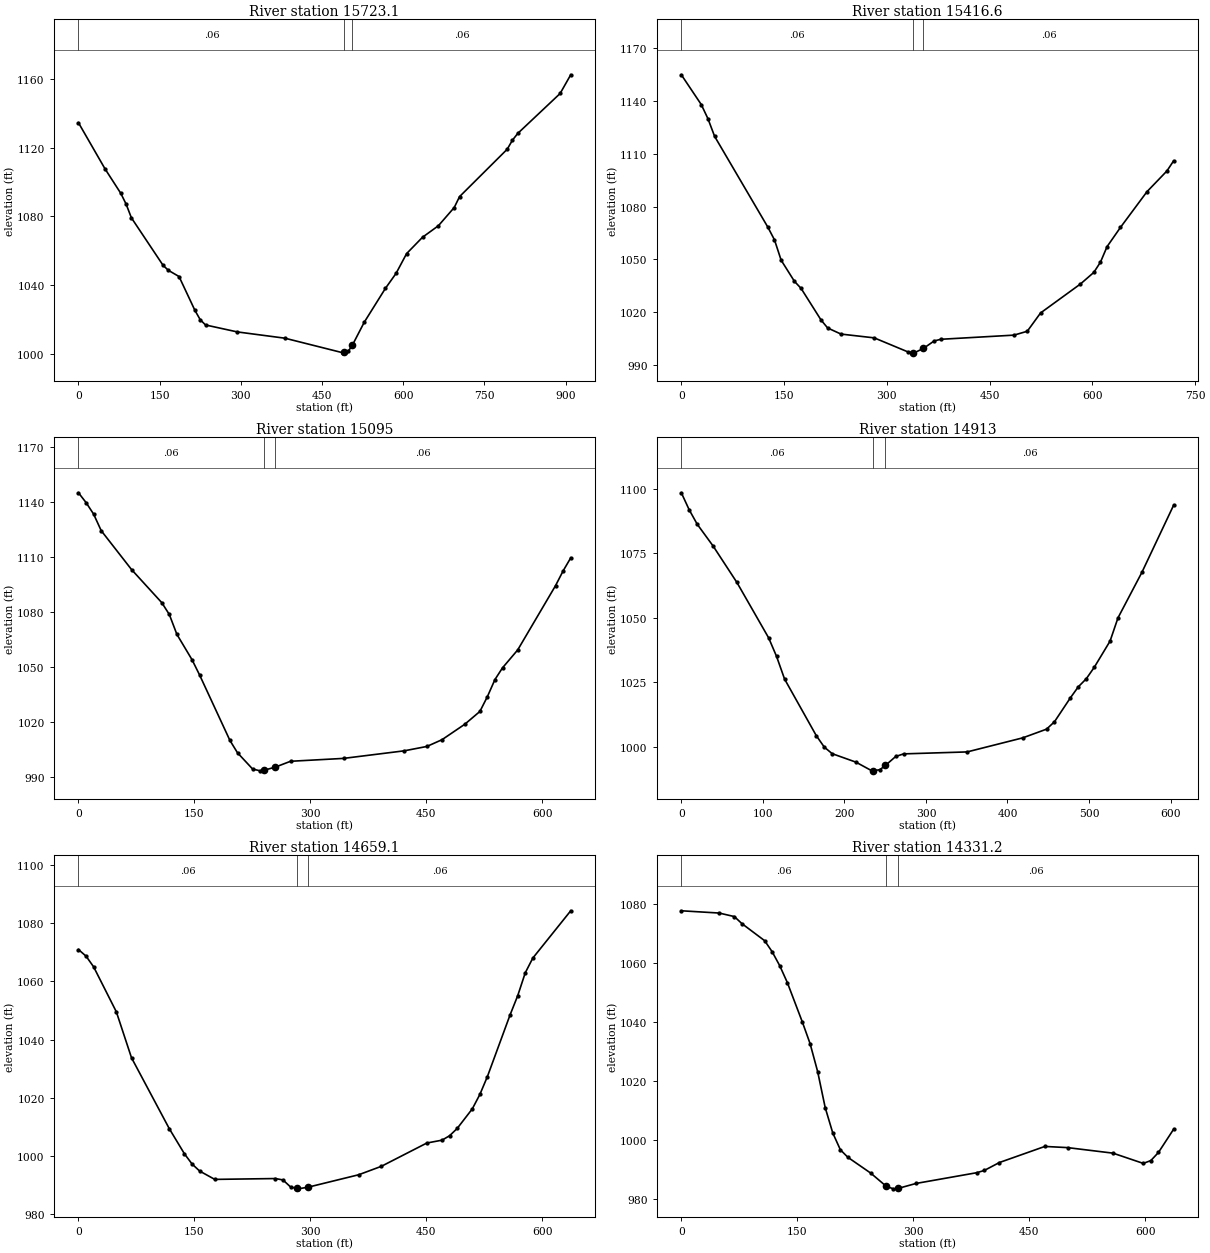
Type RM Length L Ch R = 1 ,15723.1 ,314.3,306.6,298.8
XS GIS Cut Line= 2
     1682213.647        259438.7     1683096.142      259658.085
#Sta/Elev= 30
       0 1134.52    48.9 1107.73    78.2 1093.37      88 1087.11    97.8  1079.1
   156.4 1051.37   166.2 1048.48   185.8 1044.88   215.1 1025.18   224.9 1019.74
   234.7 1016.66   293.3 1012.61   381.3 1008.95   488.9 1000.41   491.1 1000.65
   498.7 1001.46   506.1 1004.93     528 1018.28   567.1 1038.01   586.7 1046.71
   606.2 1058.25   635.6 1067.78   664.9 1074.48   694.2 1085.12     704 1091.45
     792 1119.07   801.8 1124.39   811.6 1128.32   889.8 1151.57   909.4 1162.48
#Mann= 3 , 0 , 0
       0     .06       0   491.1    .045       0   506.1     .06       0
Bank Sta=491.1,506.1
XS Rating Curve= 0 ,0
Exp/Cntr=0.3,0.1

Type RM Length L Ch R = 1 ,15416.6 ,329.7,321.6,313.4
XS GIS Cut Line= 2
     1682309.736      259895.091     1683025.022      259825.731
#Sta/Elev= 30
       0  1154.8    29.1  1137.9    38.8 1129.92    48.6 1119.84   126.2 1068.37
     136 1061.08   145.7 1049.55   165.1 1037.56   174.8 1033.55   203.9 1015.63
   213.6 1011.07   233.1 1007.61   281.6 1005.46   330.2  997.59   338.3  997.06
   339.9  996.96   353.3  999.44     369 1003.69   378.7 1004.65   485.6 1007.01
     505 1009.21   524.4 1019.59   582.7 1036.06   602.1  1042.6   611.8  1048.4
   621.5 1057.25     641 1068.14   679.8 1088.46   708.9 1100.22   718.6 1105.92
#Mann= 3 , 0 , 0
       0     .06       0   338.3    .045       0   353.3     .06       0
Bank Sta=338.3,353.3
XS Rating Curve= 0 ,0
Exp/Cntr=0.3,0.1

Type RM Length L Ch R = 1 ,15095   ,183.6,182.2,180.9
XS GIS Cut Line= 2
     1682566.014      260253.294     1683135.321      259968.228
#Sta/Elev= 30
       0 1144.98     9.8 1139.66    19.6 1133.36    29.4 1124.34    68.6 1103.16
   107.8 1085.07   117.5 1078.66   127.3 1067.81   146.9 1053.98   156.7 1045.64
   195.9    1010   205.7 1003.26   225.3   994.4   235.1  993.43   239.6  993.71
   254.6  995.46   274.3  998.64   342.8 1000.21   421.2 1004.33   450.6 1006.72
   470.2  1010.4   499.6  1018.8   519.2  1025.8   528.9 1033.86   538.7  1043.2
   548.5 1049.59   568.1 1059.32   617.1  1094.4   626.9 1102.44   636.7 1109.51
#Mann= 3 , 0 , 0
       0     .06       0   239.6    .045       0   254.6     .06       0
Bank Sta=239.6,254.6
XS Rating Curve= 0 ,0
Exp/Cntr=0.3,0.1

Type RM Length L Ch R = 1 ,14913   ,252.3,253.5,254.8
XS GIS Cut Line= 2
      1682687.24      260408.991     1683209.615      260106.367
#Sta/Elev= 30
       0 1098.37     9.7 1091.74    19.5 1086.18      39 1077.73    68.2 1063.61
   107.1 1042.15   116.8 1034.97   126.6 1026.21   165.5 1004.28   175.3  999.84
     185  997.29   214.2     994   233.7  990.64   235.3  990.71   243.4  991.07
   250.3  992.74   262.9   996.2   272.6  997.21   350.5  997.97   418.7 1003.42
   447.9 1006.79   457.6 1009.65   477.1 1018.91   486.9 1023.22   496.6  1026.3
   506.3  1030.7   525.8 1040.91   535.5 1049.91   564.8 1067.52   603.7 1093.52
#Mann= 3 , 0 , 0
       0     .06       0   235.3    .045       0   250.3     .06       0
Bank Sta=235.3,250.3
XS Rating Curve= 0 ,0
Exp/Cntr=0.3,0.1

Type RM Length L Ch R = 1 ,14659.1 ,309.3,328,346.6
XS GIS Cut Line= 2
     1682759.774      260631.915     1683329.081      260346.849
#Sta/Elev= 30
       0 1070.98     9.8 1068.72    19.6 1065.04      49 1049.56    68.6 1033.76
   117.5 1009.36   137.1 1000.71   146.9  997.23   156.7   994.8   176.3  991.93
   254.7  992.22   264.5  991.74   274.3  989.33   282.2  988.81   284.1  988.68
   297.2  989.26   362.4  993.52   391.8  996.43   450.6 1004.44   470.2 1005.42
     480 1006.94   489.8 1009.44   509.4 1016.19   519.2 1021.16   528.9 1027.28
   558.3 1048.55   568.1 1055.09   577.9    1063   587.7 1068.07   636.7 1084.32
#Mann= 3 , 0 , 0
       0     .06       0   282.2    .045       0   297.2     .06       0
Bank Sta=282.2,297.2
XS Rating Curve= 0 ,0
Exp/Cntr=0.3,0.1

Type RM Length L Ch R = 1 ,14331.2 ,312.4,321.4,330.5
XS GIS Cut Line= 2
     1682665.096      260709.437     1683262.293      260930.182
#Sta/Elev= 30
       0 1077.75      49 1076.98    68.6 1075.78    78.4 1073.38   107.8 1067.59
   117.5 1063.84   127.3  1059.1   137.1  1053.4   156.7 1039.88   166.5  1032.7
   176.3  1023.2   186.1 1010.94   195.9 1002.33   205.7  996.65   215.5  994.07
   244.9  988.74   265.1  984.24   274.3  983.39   280.1  983.51   303.6  985.22
     382  988.86   391.8  989.62   411.4  992.32   470.2  997.78   499.6  997.38
   558.3   995.5   597.5  992.02   607.3  992.99   617.1  995.73   636.7  1003.6
#Mann= 3 , 0 , 0
       0     .06       0   265.1    .045       0   280.1     .06       0
Bank Sta=265.1,280.1
XS Rating Curve= 0 ,0
Exp/Cntr=0.3,0.1

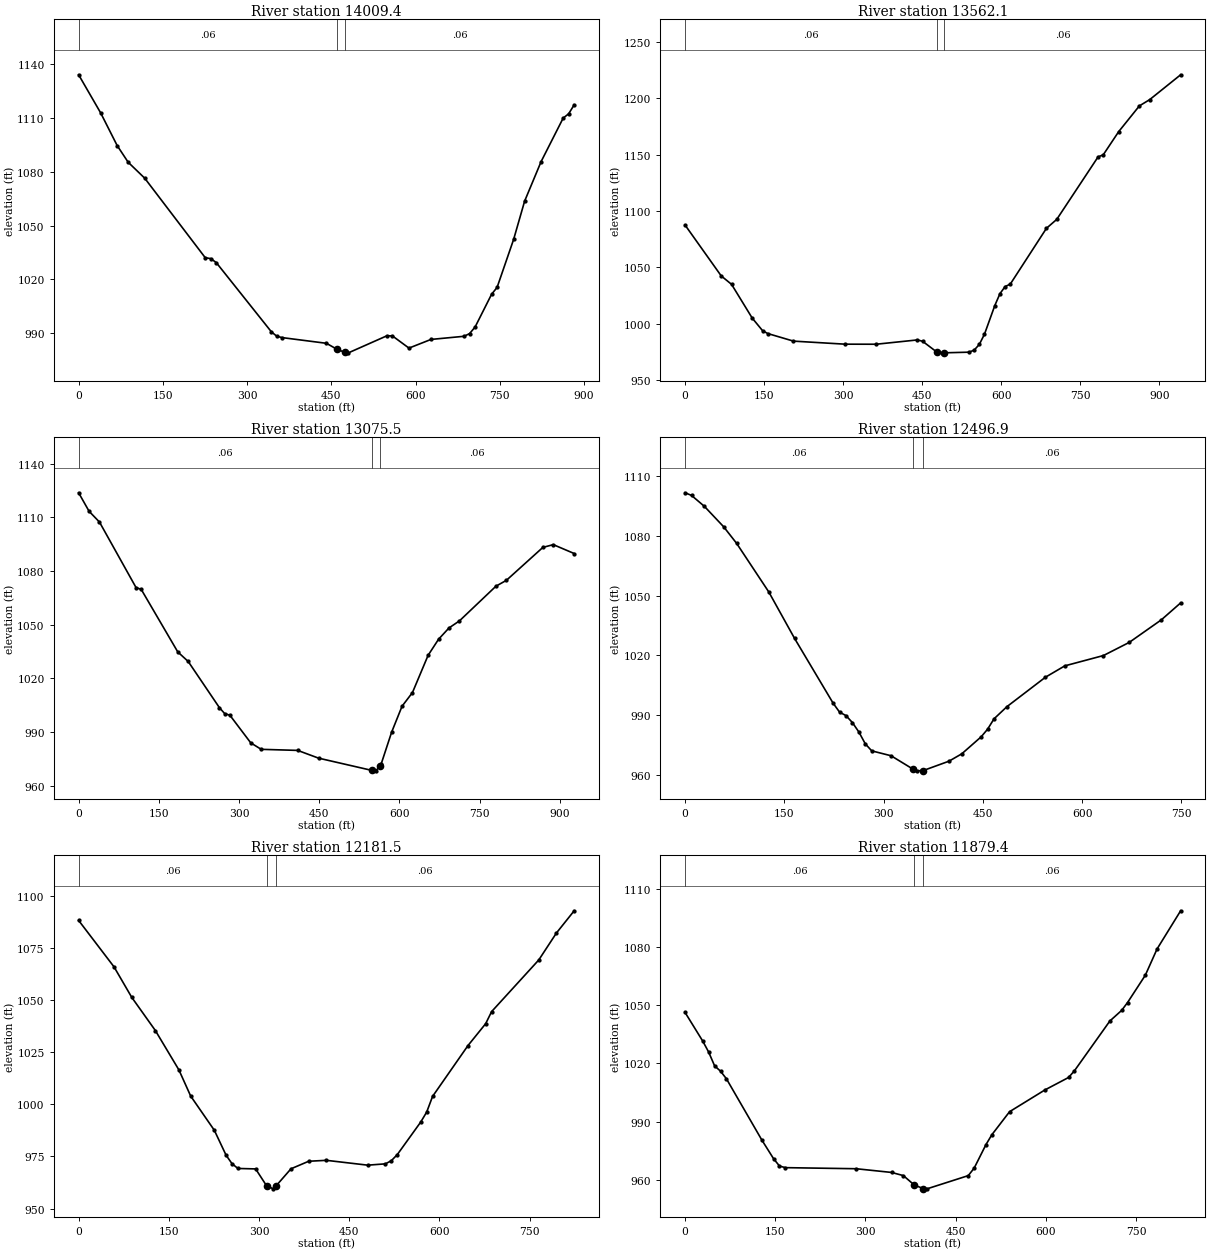
Type RM Length L Ch R = 1 ,14009.4 ,437.4,447.1,456.7
XS GIS Cut Line= 2
     1682414.373      260760.945     1683059.924      261362.216
#Sta/Elev= 30
       0 1133.87    39.2 1112.67    68.6 1094.48    88.2  1085.2   117.6 1076.34
   225.4 1032.09   235.2 1031.58     245 1029.38   343.1  990.86   352.9  988.36
   362.7  987.61   441.1  984.46   459.5  981.21   474.5  979.34   480.3  979.15
   548.9  988.65   558.7  988.55   588.1  981.79   627.3  986.61   686.2  988.36
     696  989.86   705.8  993.51   735.2 1011.75     745 1015.58   774.4 1042.26
     794 1063.57   823.4  1085.6   862.6 1109.76   872.4 1112.17   882.2 1117.15
#Mann= 3 , 0 , 0
       0     .06       0   459.5    .045       0   474.5     .06       0
#XS Ineff= 2 , 0
                          551.82          988.56
Permanent Ineff=
       F       F
Bank Sta=459.5,474.5
XS Rating Curve= 0 ,0
Exp/Cntr=0.3,0.1

Type RM Length L Ch R = 1 ,13562.1 ,485.6,486.8,487.6
XS GIS Cut Line= 2
     1682340.738      260904.184     1682690.036       261777.44
#Sta/Elev= 30
       0 1087.54    68.6 1042.46    88.2    1035   127.4 1005.08     147  993.96
   156.8   991.4   205.7  984.66   303.7  981.96   362.5  981.91   440.9  985.73
   450.7  984.54   477.3  975.15   489.9  974.28   492.3   974.3   538.8  974.87
   548.6  976.67   558.4  981.73   568.2   990.8   587.8 1016.19   597.6 1026.78
   607.4 1033.05   617.2 1035.22   685.8 1084.68   705.4 1092.62   783.8 1148.01
   793.6 1149.85     823 1170.45   862.2 1193.23   881.7 1198.76   940.5 1220.81
#Mann= 3 , 0 , 0
       0     .06       0   477.3    .045       0   492.3     .06       0
Bank Sta=477.3,492.3
XS Rating Curve= 0 ,0
Exp/Cntr=0.3,0.1

Type RM Length L Ch R = 1 ,13075.5 ,598.5,578.5,558.4
XS GIS Cut Line= 2
      1682003.21      261008.098     1682263.928      261897.407
#Sta/Elev= 30
       0 1123.77    19.5 1113.44      39 1107.38   107.3 1070.79   117.1 1069.71
   185.4 1034.76   204.9 1029.42   263.4 1003.53   273.1 1000.28   282.9  999.33
   321.9   983.9   341.4  980.28   409.7  979.68   448.7  975.35   548.3   968.5
     556  968.25   563.3  971.12   565.8   972.1   585.3  989.85   604.8 1004.38
   624.3 1012.04   653.6  1032.9   673.1 1041.85   692.6 1048.17   712.1 1052.11
   780.4 1071.52   799.9 1074.79   868.2 1093.23   887.7 1094.76   926.7  1089.8
#Mann= 3 , 0 , 0
       0     .06       0   548.3    .045       0   563.3     .06       0
Bank Sta=548.3,563.3
XS Rating Curve= 0 ,0
Exp/Cntr=0.3,0.1

Type RM Length L Ch R = 1 ,12496.9 ,319.2,315.4,311.6
XS GIS Cut Line= 2
     1681384.464      261700.275     1682075.699      261988.047
#Sta/Elev= 30
       0 1101.74     9.7 1100.42    29.2  1094.9    58.3 1084.64    77.8 1076.35
   126.4 1051.93   165.3 1028.62   223.6  996.04   233.4  991.51   243.1  989.77
   252.8  986.26   262.6  981.51   272.3  975.56     282  972.06   311.2   969.6
   344.6  962.82   350.1  962.02   359.6  962.14   398.7  966.87   418.1  970.59
   447.3  979.11     457  982.94   466.8  988.17   486.2  994.26   544.5 1009.08
   573.7 1014.77   632.1 1019.96     671 1026.55   719.6 1037.91   748.7  1046.4
#Mann= 3 , 0 , 0
       0     .06       0   344.6    .045       0   359.6     .06       0
Bank Sta=344.6,359.6
XS Rating Curve= 0 ,0
Exp/Cntr=0.3,0.1

Type RM Length L Ch R = 1 ,12181.5 ,294.3,301.9,309.6
XS GIS Cut Line= 2
     1681280.618      262055.979     1682083.814      262240.988
#Sta/Elev= 30
       0 1088.24    58.9 1065.94    88.3 1051.35   127.6 1035.41   166.8  1016.5
   186.4 1003.94   225.7  987.54   245.3  975.55   255.1  971.52   264.9  969.22
   294.4     969   312.6   960.9   323.8  959.44   327.6   960.6   353.2  969.06
   382.7  972.68   412.1  973.12   480.8   970.8   510.2  971.43     520  972.92
   529.9  975.83   569.1  991.54   578.9  996.28   588.7  1003.8   647.6  1028.2
     677  1038.7   686.9 1044.49   765.4  1069.3   794.8 1082.25   824.2 1092.87
#Mann= 3 , 0 , 0
       0     .06       0   312.6    .045       0   327.6     .06       0
Bank Sta=312.6,327.6
XS Rating Curve= 0 ,0
Exp/Cntr=0.3,0.1

Type RM Length L Ch R = 1 ,11879.4 ,388.4,402.3,416.1
XS GIS Cut Line= 2
     1681240.411      262218.802      1681937.49      262658.613
#Sta/Elev= 30
       0 1046.27    29.4 1031.49    39.2 1025.85    49.1 1018.73    58.9 1016.01
    68.7  1012.1   127.6  980.51   147.2  970.83     157  967.07   166.8  966.24
   284.6  965.68   343.4  963.77     363  962.14   381.3  957.26   396.3  955.43
   402.3  955.31     471  962.13   480.8  966.01   500.4  978.12   510.2  983.21
   539.7  995.11   598.6 1006.35   637.8 1012.75   647.6 1016.22   706.5 1041.89
   726.1 1047.36   735.9 1051.41   765.4 1065.46     785 1079.05   824.2 1098.74
#Mann= 3 , 0 , 0
       0     .06       0   381.3    .045       0   396.3     .06       0
Bank Sta=381.3,396.3
XS Rating Curve= 0 ,0
Exp/Cntr=0.3,0.1

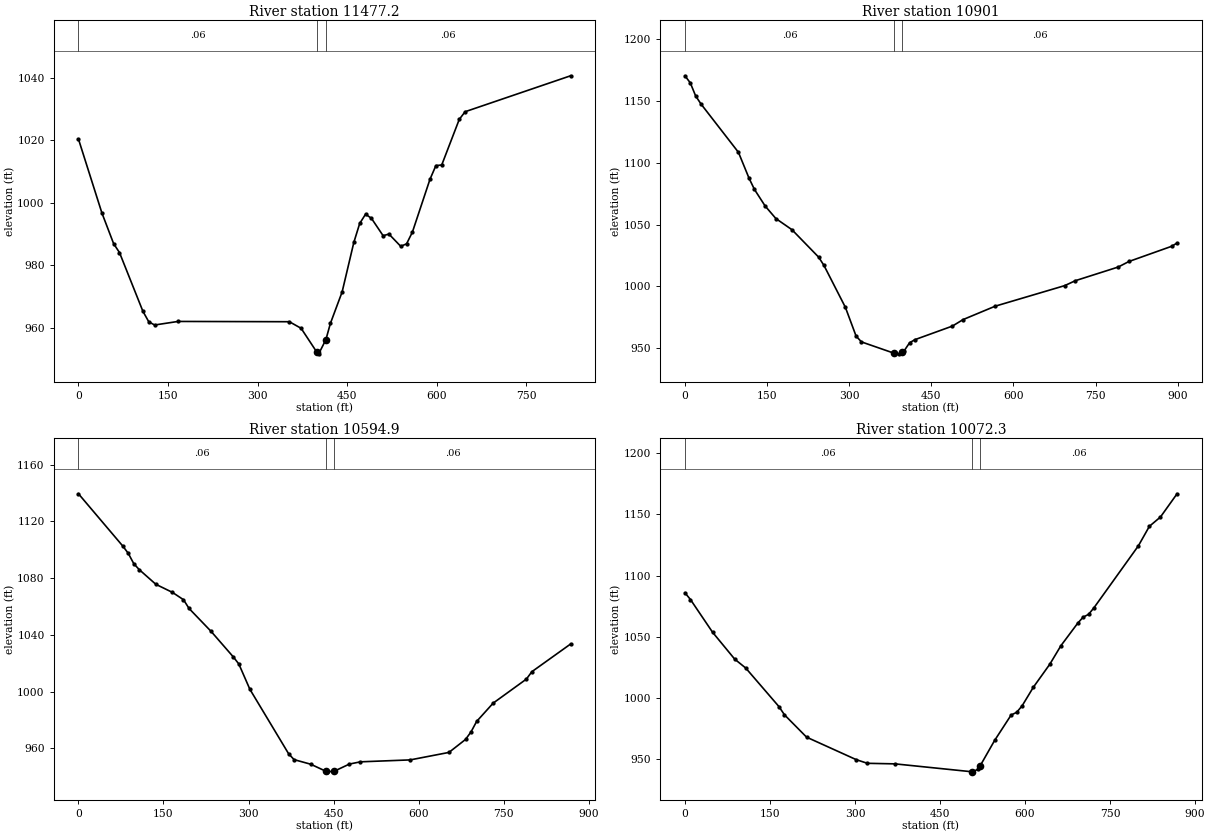
Type RM Length L Ch R = 1 ,11477.2 ,599.7,576,552.2
XS GIS Cut Line= 2
     1681172.624      262334.324     1681498.278      263091.491
#Sta/Elev= 30
       0  1020.4    39.2  996.78    58.9  986.92    68.7  984.08   107.9  965.29
   117.8   961.9   127.6  960.89   166.8  962.03   353.2  961.94   372.9  959.83
   399.4  952.14   402.3  951.66   414.4  956.21   421.9  961.38   441.6  971.49
   461.2  987.34     471  993.39   480.8  996.35   490.6  995.05   510.2  989.48
     520  989.99   539.7  986.08   549.5  986.87   559.3  990.64   588.7 1007.53
   598.6 1011.91   608.4 1012.11   637.8 1026.73   647.6 1029.16   824.2 1040.66
#Mann= 3 , 0 , 0
       0     .06       0   399.4    .045       0   414.4     .06       0
#XS Ineff= 2 , 0
          342.78  961.92
Permanent Ineff=
       F       F
Bank Sta=399.4,414.4
XS Rating Curve= 0 ,0
Exp/Cntr=0.3,0.1

Type RM Length L Ch R = 1 ,10901   ,303.7,306,308.2
XS GIS Cut Line= 2
     1680581.909      263002.233     1681474.596      263106.938
#Sta/Elev= 30
       0 1169.97     9.8 1164.25    19.5  1153.8    29.3 1147.22    97.7 1108.26
   117.2 1087.24     127 1078.28   146.5 1064.92   166.1 1054.81   195.4 1045.83
   244.2 1023.69     254 1016.94   293.1  983.16   312.6  959.99   322.4  955.31
   381.6  946.23   390.8  945.68   396.6  947.21   400.6  948.26   410.3  954.62
   420.1  957.13   488.5  968.07     508  973.31   566.6  984.11   693.6  1000.7
   713.2 1004.71   791.3  1015.7   810.9 1020.17     889 1032.44   898.8 1035.07
#Mann= 3 , 0 , 0
       0     .06       0   381.6    .045       0   396.6     .06       0
Bank Sta=381.6,396.6
XS Rating Curve= 0 ,0
Exp/Cntr=0.3,0.1

Type RM Length L Ch R = 1 ,10594.9 ,509.5,522.4,535.4
XS GIS Cut Line= 2
     1680538.736      263260.324     1681387.616      263442.402
#Sta/Elev= 30
       0 1139.51      78 1102.75    87.8 1097.57    97.6 1090.23   107.3 1086.02
   136.6 1075.68   165.8    1070   185.3 1064.84   195.1 1058.67   234.1 1042.46
   273.1 1024.55   282.9 1019.55   302.4  1001.7   370.7  956.29   380.4  952.11
   409.7  948.89   436.6   943.9     439  943.51   451.6  944.03     478  948.99
   497.5  950.57   585.3  951.93   653.6   957.2   682.8  966.33   692.6  971.69
   702.4  979.02   731.6  991.94   790.2 1008.88   799.9  1014.1   868.2 1033.61
#Mann= 3 , 0 , 0
       0     .06       0   436.6    .045       0   451.6     .06       0
Bank Sta=436.6,451.6
XS Rating Curve= 0 ,0
Exp/Cntr=0.3,0.1

Type RM Length L Ch R = 1 ,10072.3 ,426.1,426.3,426.6
XS GIS Cut Line= 2
     1680533.797      263467.413     1681143.464      264085.519
#Sta/Elev= 30
       0  1085.9     9.8 1080.36    48.8 1053.63    87.8  1031.7   107.3  1024.4
   165.8  992.96   175.6  986.22   214.6  967.96   302.4  949.55   321.9   946.6
   370.7  946.14   505.7  939.72   507.3  939.63     517  941.75   520.7  944.43
   546.3  965.24   575.5  986.06   585.3  988.26     595  993.66   614.6 1008.69
   643.8  1027.6   663.3 1042.67   692.6 1060.83   702.4 1065.96   712.1 1068.26
   721.9 1073.84   799.9  1124.2   819.4 1140.21   838.9 1147.78   868.2 1166.76
#Mann= 3 , 0 , 0
       0     .06       0   505.7    .045       0   520.7     .06       0
Bank Sta=505.7,520.7
XS Rating Curve= 0 ,0
Exp/Cntr=0.3,0.1