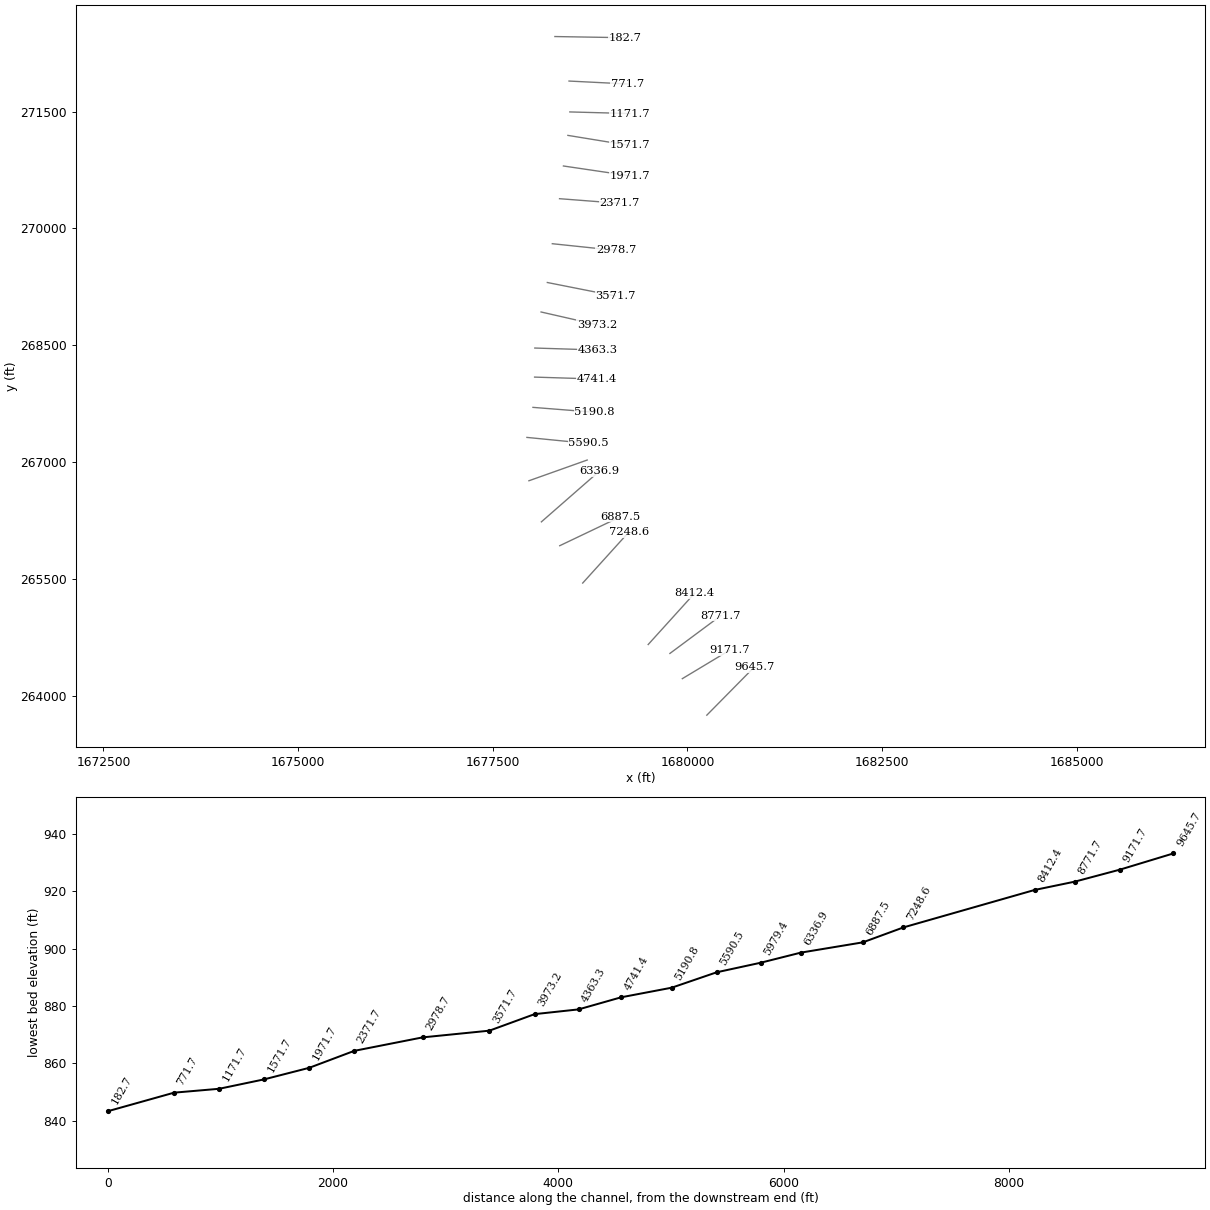
HEC-RAS study ISLANDCRK.prj: ISLANDCRK

--- ISLANDCRK.g01 (geometry) --- (continued)

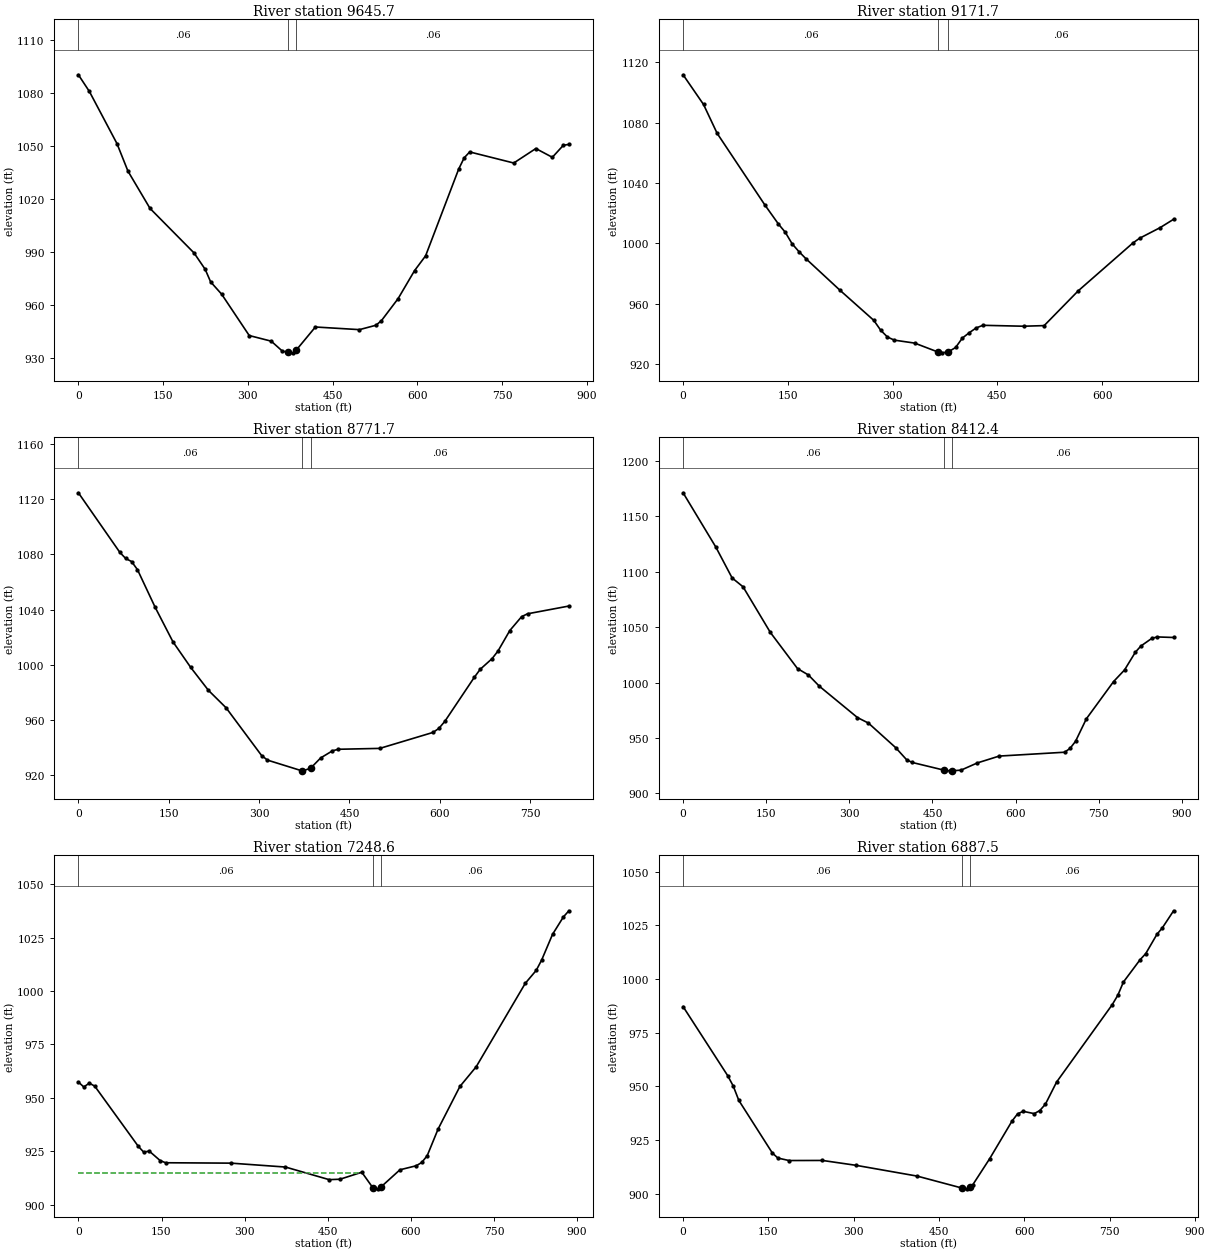
Type RM Length L Ch R = 1 ,9645.7  ,479.7,474.1,468.4
XS GIS Cut Line= 2
     1680249.017      263748.305     1680858.684      264366.411
#Sta/Elev= 30
       0 1090.51    19.5 1081.05    68.3 1051.57    87.8 1035.95   126.8 1014.89
   204.8  989.66   224.4  980.44   234.1  973.31   253.6  966.34   302.4  942.95
   341.4  939.76   360.9  934.17   370.3  933.45   380.4  933.16   385.3  934.58
   419.5  947.78   497.5  946.29   526.8  948.78   536.5  951.41   565.8  963.79
     595  979.67   614.6  988.07   673.1 1037.13   682.8 1043.49   692.6 1046.85
   770.6 1040.58   809.7 1048.77   838.9 1043.81   858.4 1050.62   868.2 1051.11
#Mann= 3 , 0 , 0
       0     .06       0   370.3    .045       0   385.3     .06       0
Bank Sta=370.3,385.3
XS Rating Curve= 0 ,0
Exp/Cntr=0.3,0.1

Type RM Length L Ch R = 1 ,9171.7  ,397.8,400,402.1
XS GIS Cut Line= 2
     1679934.595      264217.253     1680536.422      264579.169
#Sta/Elev= 30
       0 1111.71    29.3 1092.03    48.8 1072.89     117 1025.54   136.6  1012.8
   146.3  1007.4   156.1  999.76   165.8  994.61   175.6     990   224.3  969.12
   273.1  949.02   282.9  942.51   292.6     938   302.4  935.94   331.6  933.97
   364.8  928.09   370.6  927.52   379.8  928.18   390.2  931.06   399.9  937.32
   409.7  940.83   419.4  943.96   429.2  945.76   487.7  945.15     517  945.56
   565.7  968.57   643.8 1000.19   653.5 1003.39   682.8  1010.4   702.3 1015.99
#Mann= 3 , 0 , 0
       0     .06       0   364.8    .045       0   379.8     .06       0
Bank Sta=364.8,379.8
XS Rating Curve= 0 ,0
Exp/Cntr=0.3,0.1

Type RM Length L Ch R = 1 ,8771.7  ,354.8,359.2,363.6
XS GIS Cut Line= 2
     1679775.147       264541.09     1680428.714      265026.643
#Sta/Elev= 30
       0 1124.53    68.7 1081.49    78.5 1076.99    88.3 1074.78    98.1 1068.89
   127.5 1041.62     157 1016.68   186.4  998.21   215.8  981.62   245.2  968.95
   304.1  934.43   313.9   931.1   370.5  923.42   372.8  923.34   385.5  925.26
   402.2  932.68   421.8  937.84   431.6  938.95   500.3  939.58   588.6  951.13
   598.4  954.05   608.2   959.1   657.2  991.01     667  996.81   686.7 1004.52
   696.5 1010.02   716.1 1024.84   735.7 1034.89   745.5 1036.96   814.2 1042.58
#Mann= 3 , 0 , 0
       0     .06       0   370.5    .045       0   385.5     .06       0
Bank Sta=370.5,385.5
XS Rating Curve= 0 ,0
Exp/Cntr=0.3,0.1

Type RM Length L Ch R = 1 ,8412.4  ,1163.6,1163.6,1163.5
XS GIS Cut Line= 2
     1679496.194      264655.733     1680090.123      265311.944
#Sta/Elev= 30
       0 1171.12      59 1122.25    88.5 1094.33   108.2 1086.35   157.4 1045.26
   206.5 1012.61   226.2 1006.83   245.9  996.71   314.7  968.44   334.4  963.49
   383.5  941.38   403.2  930.53     413  928.03     470  921.14   481.9  920.42
     485  920.46   501.5  921.03     531  927.56   570.4  933.73   688.4   937.2
   698.2  940.63   708.1  946.99   727.7  967.33   776.9 1000.96   796.6 1011.39
   816.2 1027.44   826.1 1032.95   845.7 1039.83   855.6 1041.15   885.1 1040.65
#Mann= 3 , 0 , 0
       0     .06       0     470    .045       0     485     .06       0
Bank Sta=470,485
XS Rating Curve= 0 ,0
Exp/Cntr=0.3,0.1

Type RM Length L Ch R = 1 ,7248.6  ,369.7,361,352.2
XS GIS Cut Line= 2
     1678655.199      265444.939     1679249.128       266101.15
#Sta/Elev= 30
       0  957.37     9.8  955.08    19.7  956.86    29.5  955.47   108.2  927.26
     118  924.55   127.8  925.08   147.5  920.63   157.4   919.6   275.4  919.42
   373.7  917.59   452.4   911.7     472  911.88   511.4  915.16   531.5  907.85
   540.9  907.39   546.5  908.38   580.2   916.3   609.7   918.2   619.6  919.75
   629.4  922.89   649.1  935.38   688.4   955.3   717.9  964.56   806.4 1003.59
   826.1 1009.64   835.9 1014.46   855.6 1026.52   875.2 1034.68   885.1 1037.55
#Mann= 3 , 0 , 0
       0     .06       0   531.5    .045       0   546.5     .06       0
#XS Ineff= 2 , 0
          507.53  914.93
Permanent Ineff=
       F       F
Bank Sta=531.5,546.5
XS Rating Curve= 0 ,0
Exp/Cntr=0.3,0.1

Type RM Length L Ch R = 1 ,6887.5  ,544.4,550.6,556.7
XS GIS Cut Line= 2
     1678360.182       265924.44     1679138.431      266295.569
#Sta/Elev= 30
       0  987.17    78.4  954.97    88.2   950.1      98  943.41   156.8  918.94
   166.6  916.54   186.2  915.38     245  915.42   303.7  913.16   411.5  908.12
     490  902.56   499.7  902.18     505  903.27   509.5   904.2   538.9  916.23
   578.1  933.74   587.9  937.13   597.7  938.33   617.3  937.25   627.1  938.71
   636.9  941.66   656.5  951.96   754.4  988.09   764.2  992.47     774  998.62
   803.4 1009.06   813.2 1011.86   832.8 1020.82   842.6 1023.96   862.2 1031.85
#Mann= 3 , 0 , 0
       0     .06       0     490    .045       0     505     .06       0
Bank Sta=490,505
XS Rating Curve= 0 ,0
Exp/Cntr=0.3,0.1

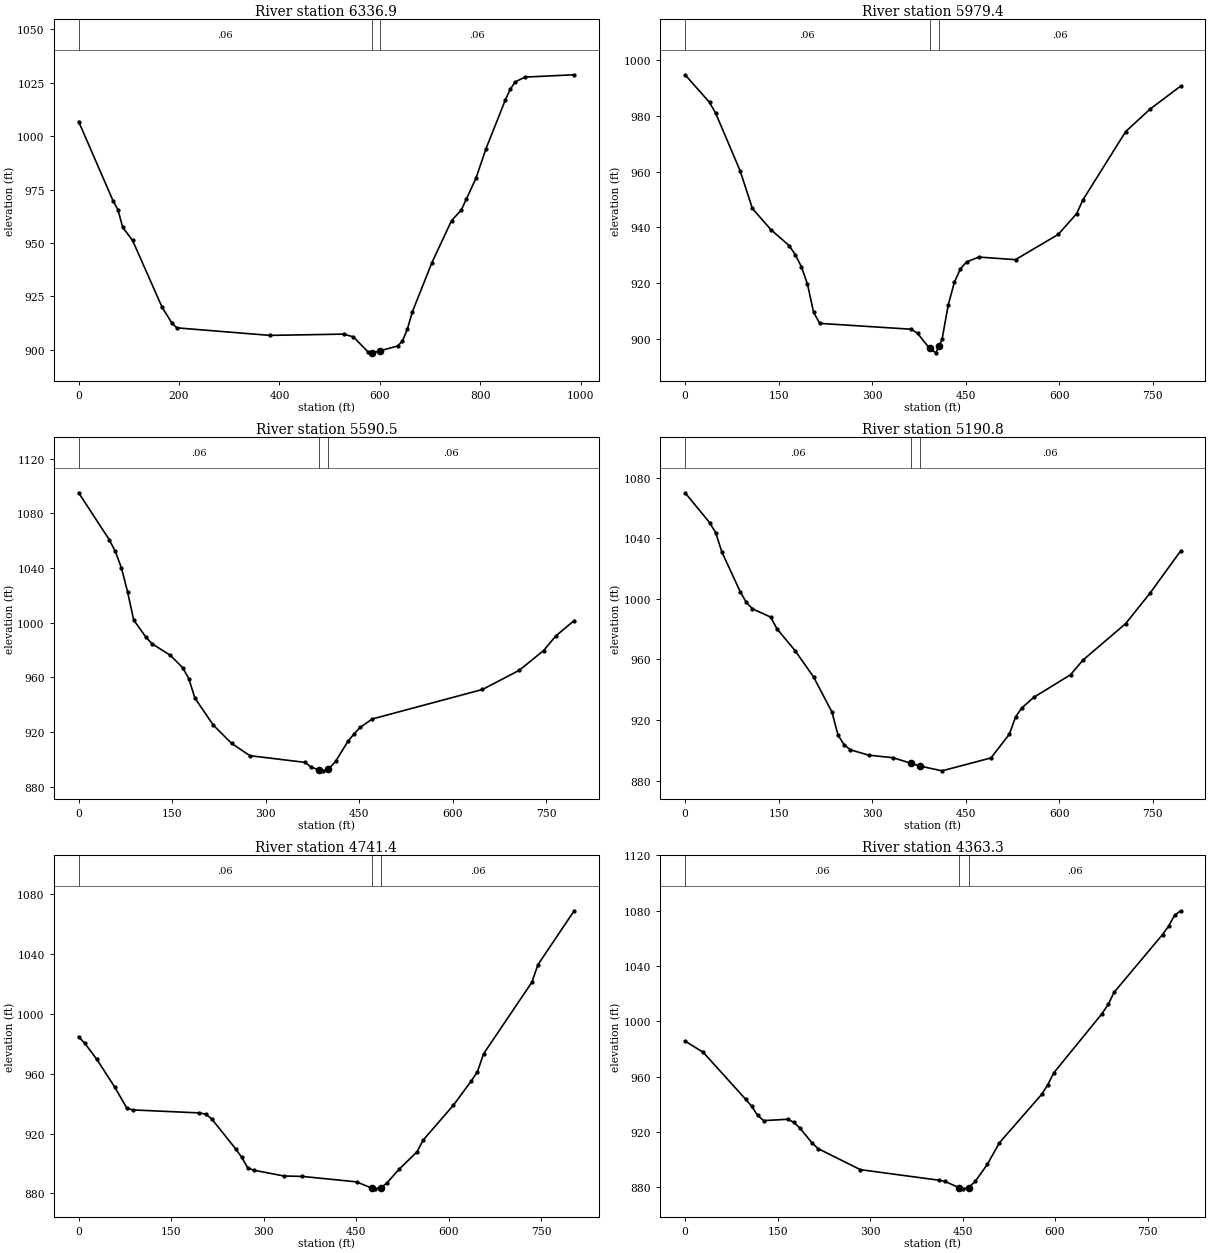
Type RM Length L Ch R = 1 ,6336.9  ,366,357.5,348.9
XS GIS Cut Line= 2
      1678124.67      266230.895      1678867.66      266880.489
#Sta/Elev= 30
       0 1006.82    68.4  969.81    78.2  965.58    87.9  957.28   107.5  951.16
   166.1  919.97   185.7  912.58   195.4  910.29   381.1  906.76   527.7  907.36
   547.2  906.06   576.5     899   584.4  898.68   586.3   898.6   599.4   899.5
   635.1  901.78   644.9  904.09   654.7  909.72   664.5  917.71   703.6   940.8
   742.6  960.41   762.2  965.47     772  970.45   791.5   980.4     811  993.94
   850.1 1017.08   859.9 1022.08   869.7 1025.39   889.2 1027.62   986.9 1028.69
#Mann= 3 , 0 , 0
       0     .06       0   584.4    .045       0   599.4     .06       0
Bank Sta=584.4,599.4
XS Rating Curve= 0 ,0
Exp/Cntr=0.3,0.1

Type RM Length L Ch R = 1 ,5979.4  ,398.9,388.9,379
XS GIS Cut Line= 2
     1677964.409      266758.549     1678713.133      267024.766
#Sta/Elev= 30
       0  994.66    39.2  984.77      49   980.9    88.3  960.24   107.9  946.78
   137.4  939.23   166.8  933.49   176.6  930.25   186.4  925.97   196.2  919.67
     206  909.65   215.8  905.62     363  903.52   372.8  902.02   392.1  896.64
   402.2  895.07   407.1  897.46     412  899.86   421.8  912.08   431.7  920.32
   441.5  925.16   451.3  927.63   470.9  929.38   529.8  928.44   598.4   937.5
   627.9  944.93   637.7  949.77   706.4  974.29   745.6  982.37   794.6   990.6
#Mann= 3 , 0 , 0
       0     .06       0   392.1    .045       0   407.1     .06       0
Bank Sta=392.1,407.1
XS Rating Curve= 0 ,0
Exp/Cntr=0.3,0.1

Type RM Length L Ch R = 1 ,5590.5  ,399.2,399.6,400.1
XS GIS Cut Line= 2
     1677938.656      267315.257     1678729.441      267237.037
#Sta/Elev= 30
       0 1095.02      49 1060.82    58.9 1052.12    68.7 1039.99    78.5 1022.52
    88.3 1002.01   107.9  989.47   117.7  984.66   147.2  976.16   166.8  967.15
   176.6   959.2   186.4  945.03   215.8  925.24   245.3  911.81   274.7  902.83
     363  897.94   372.8  894.57   385.5  892.31   392.4  891.76   400.5  892.92
     412  898.65   431.7  913.25   441.5  918.71   451.3  923.47   470.9  929.68
   647.5  951.22   706.4  965.22   745.6  979.71   765.2  990.39   794.6 1001.61
#Mann= 3 , 0 , 0
       0     .06       0   385.5    .045       0   400.5     .06       0
Bank Sta=385.5,400.5
XS Rating Curve= 0 ,0
Exp/Cntr=0.3,0.1

Type RM Length L Ch R = 1 ,5190.8  ,448.2,449.3,450.3
XS GIS Cut Line= 2
       1678016.5      267701.019     1678808.668      267638.337
#Sta/Elev= 30
       0 1070.05    39.2 1050.41      49 1043.76    58.9 1030.96    88.3  1004.8
    98.1  997.71   107.9  993.44   137.4  987.91   147.2  980.26   176.6  965.66
     206  948.38   235.4   925.3   245.3  909.91   255.1   903.6   264.9  900.31
   294.3  896.75   333.6  895.05   361.8  891.42   376.8  889.54     412  886.39
   490.5  894.93     520  910.62   529.8  921.85   539.6  927.84   559.2  934.97
   618.1  949.88   637.7  959.43   706.4  983.62   745.6 1003.81   794.6 1031.64
#Mann= 3 , 0 , 0
       0     .06       0   361.8    .045       0   376.8     .06       0
Bank Sta=361.8,376.8
XS Rating Curve= 0 ,0
Exp/Cntr=0.3,0.1

Type RM Length L Ch R = 1 ,4741.4  ,378.2,377.9,377.7
XS GIS Cut Line= 2
     1678037.262      268089.691     1678840.558       268064.42
#Sta/Elev= 30
       0  984.67     9.8  980.45    29.4  969.69    58.8  950.91    78.4  936.83
    88.2  935.81     196   933.8   205.8  933.02   215.6  929.92   254.8  909.69
   264.6  904.06   274.4  897.02   284.2   895.5   333.2  891.62   362.6  891.36
   450.8   887.7   475.6   883.5   480.3  883.04   490.6  883.83   499.9  886.93
   519.5  896.04   548.9  907.82   558.7  915.59   607.7   938.9   637.1  955.32
   646.9  961.43   656.7  973.29   735.1 1021.16   744.9  1032.9   803.7 1068.96
#Mann= 3 , 0 , 0
       0     .06       0   475.6    .045       0   490.6     .06       0
Bank Sta=475.6,490.6
XS Rating Curve= 0 ,0
Exp/Cntr=0.3,0.1

Type RM Length L Ch R = 1 ,4363.3  ,394.2,390.1,386
XS GIS Cut Line= 2
     1678040.069      268462.941     1678843.365       268437.67
#Sta/Elev= 30
       0   985.7    29.4  977.58      98  943.73   107.8  938.66   117.6  931.99
   127.4  928.18   166.6  929.17   176.4   926.9   186.2  922.77   205.8  912.13
   215.6  907.95   284.2  892.71   411.6  885.08   421.4  884.22   444.8   879.6
   450.8  878.83   459.8  879.77   470.4  884.15   490.1  896.45   509.7   912.1
   578.3  947.17   588.1  954.05   597.9   962.7   676.3 1005.62   686.1 1012.23
   695.9 1021.05   774.3 1062.79   784.1 1068.82   793.9 1076.73   803.7 1079.99
#Mann= 3 , 0 , 0
       0     .06       0   444.8    .045       0   459.8     .06       0
Bank Sta=444.8,459.8
XS Rating Curve= 0 ,0
Exp/Cntr=0.3,0.1

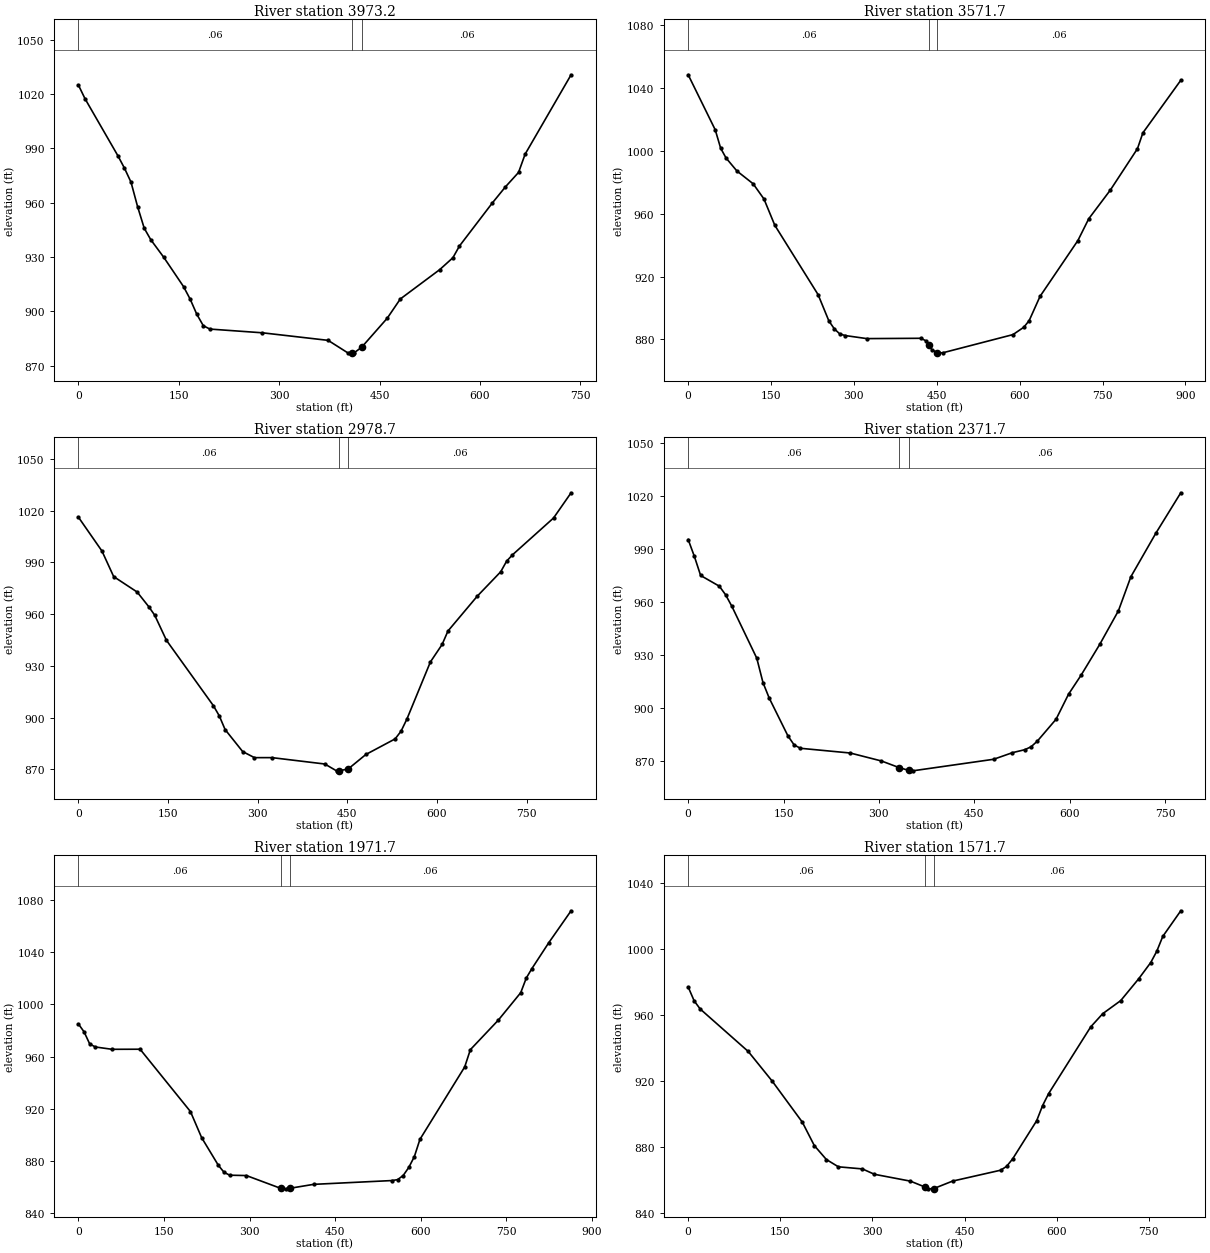
Type RM Length L Ch R = 1 ,3973.2  ,400.4,401.6,402.8
XS GIS Cut Line= 2
     1678120.528      268925.809     1678838.256      268762.257
#Sta/Elev= 30
       0 1024.87     9.8  1017.4    58.9  985.94    68.7   979.1    78.5  971.36
    88.3  957.89    98.2  945.99     108  939.63   127.6  929.82     157  913.72
   166.9   906.8   176.7  898.54   186.5  892.16   196.3   890.3   274.8  888.24
     373  884.07   402.4  877.18   408.2  877.23   412.2  877.27   423.2  880.29
   461.3  896.26   480.9   906.9   539.8  923.11   559.5  929.68   569.3  936.15
   618.4  959.89     638  968.79   657.6  976.76   667.4  986.83   736.1 1030.64
#Mann= 3 , 0 , 0
       0     .06       0   408.2    .045       0   423.2     .06       0
Bank Sta=408.2,423.2
XS Rating Curve= 0 ,0
Exp/Cntr=0.3,0.1

Type RM Length L Ch R = 1 ,3571.7  ,592.7,593.2,593.7
XS GIS Cut Line= 2
     1678200.939      269304.469     1679075.533       269131.21
#Sta/Elev= 30
       0 1048.38      49 1013.33    58.8 1001.64    68.6   995.4    88.2  987.16
   117.6  979.01   137.2  969.32   156.8  952.59   235.1  908.49   254.7  891.71
   264.5   886.7   274.3  883.47   284.1  882.43   323.3  880.48   421.3  880.68
   431.1  878.93   435.7  876.37   440.9  873.47   450.7  871.52   460.5  871.42
   587.9  883.03   607.5  887.72   617.2  891.94   636.8  907.33   705.4  942.91
     725  956.74   764.2  975.06   813.2 1001.36     823 1011.42   891.6 1044.87
#Mann= 3 , 0 , 0
       0     .06       0   435.7    .045       0   450.7     .06       0
Bank Sta=435.7,450.7
XS Rating Curve= 0 ,0
Exp/Cntr=0.3,0.1

Type RM Length L Ch R = 1 ,2978.7  ,604.7,606.3,608
XS GIS Cut Line= 2
     1678264.912      269802.565     1679084.948      269716.634
#Sta/Elev= 30
       0 1016.12    39.3  996.54    58.9  981.72    98.2  972.77   117.8  964.19
   127.6  959.33   147.2  944.79   225.8  906.86   235.6     901   245.4  893.02
   274.8  880.26   294.5  876.73   323.9  876.74   412.3  873.04   431.9  869.08
   436.7  869.08   451.7  870.25     481  878.56     530  887.61   539.9  892.08
   549.7  899.11     589  932.22   608.6  942.35   618.4  950.16   667.5  970.39
   706.7  984.52   716.6  990.68   726.4  994.35   795.1 1015.69   824.5 1030.33
#Mann= 3 , 0 , 0
       0     .06       0   436.7    .045       0   451.7     .06       0
Bank Sta=436.7,451.7
XS Rating Curve= 0 ,0
Exp/Cntr=0.3,0.1

Type RM Length L Ch R = 1 ,2371.7  ,401.5,400,398.4
XS GIS Cut Line= 2
     1678357.753      270380.657     1679130.338      270321.259
#Sta/Elev= 30
       0  995.48     9.8  985.86    19.6   975.1      49  969.03    58.8  964.21
    68.7  957.65   107.9  928.23   117.7  914.38   127.5   905.6   156.9  884.21
   166.7  879.06   176.6  877.17     255  874.49   304.1  869.97     332   866.2
     347  864.65   353.1  864.39   480.6  870.95     510  874.68   529.6  876.38
   539.5  878.05   549.3  881.25   578.7  893.63   598.3   907.8   617.9  918.49
   647.4  936.05   676.8   955.1   696.4   974.4   735.6  999.02   774.9 1021.97
#Mann= 3 , 0 , 0
       0     .06       0     332    .045       0     347     .06       0
Bank Sta=332,347
XS Rating Curve= 0 ,0
Exp/Cntr=0.3,0.1

Type RM Length L Ch R = 1 ,1971.7  ,399.5,400.2,401
XS GIS Cut Line= 2
     1678407.634      270800.726     1679261.943      270674.386
#Sta/Elev= 30
       0  984.92     9.8  978.96    19.6  969.74    29.4  967.36    58.9  965.56
     108  965.63   196.3  917.78   215.9  897.77   245.3  876.48   255.2  871.17
     265  868.95   294.4  868.67   355.1  858.76   363.1  858.48   370.1  858.87
   412.2  861.92   549.6  864.84   559.4  865.54   569.2   868.7     579  874.87
   588.8  883.18   598.6  896.46   677.1  952.05     687  965.29     736  987.94
   775.3 1009.02   785.1 1020.31   794.9 1027.52   824.4 1047.32   863.6 1071.87
#Mann= 3 , 0 , 0
       0     .06       0   355.1    .045       0   370.1     .06       0
Bank Sta=355.1,370.1
XS Rating Curve= 0 ,0
Exp/Cntr=0.3,0.1

Type RM Length L Ch R = 1 ,1571.7  ,397.6,399.6,401.7
XS GIS Cut Line= 2
     1678465.037       271193.67     1679256.681      271064.467
#Sta/Elev= 30
       0  977.07     9.8   968.6    19.6  963.68    97.8   937.9     137   919.8
   185.9  894.94   205.4  880.73     225  872.28   244.6  867.84   283.7  866.56
   303.2   863.3   361.9  859.13   384.8  855.68   391.3  854.46   399.8  854.61
   430.4  859.15   508.7  865.77   518.4  868.08   528.2  872.58   567.4   895.8
   577.1  905.03   586.9   912.3   655.4  952.81     675  960.85   704.3  968.79
   733.6  982.06   753.2  991.92     763  998.77   772.8 1007.79   802.1 1023.35
#Mann= 3 , 0 , 0
       0     .06       0   384.8    .045       0   399.8     .06       0
Bank Sta=384.8,399.8
XS Rating Curve= 0 ,0
Exp/Cntr=0.3,0.1

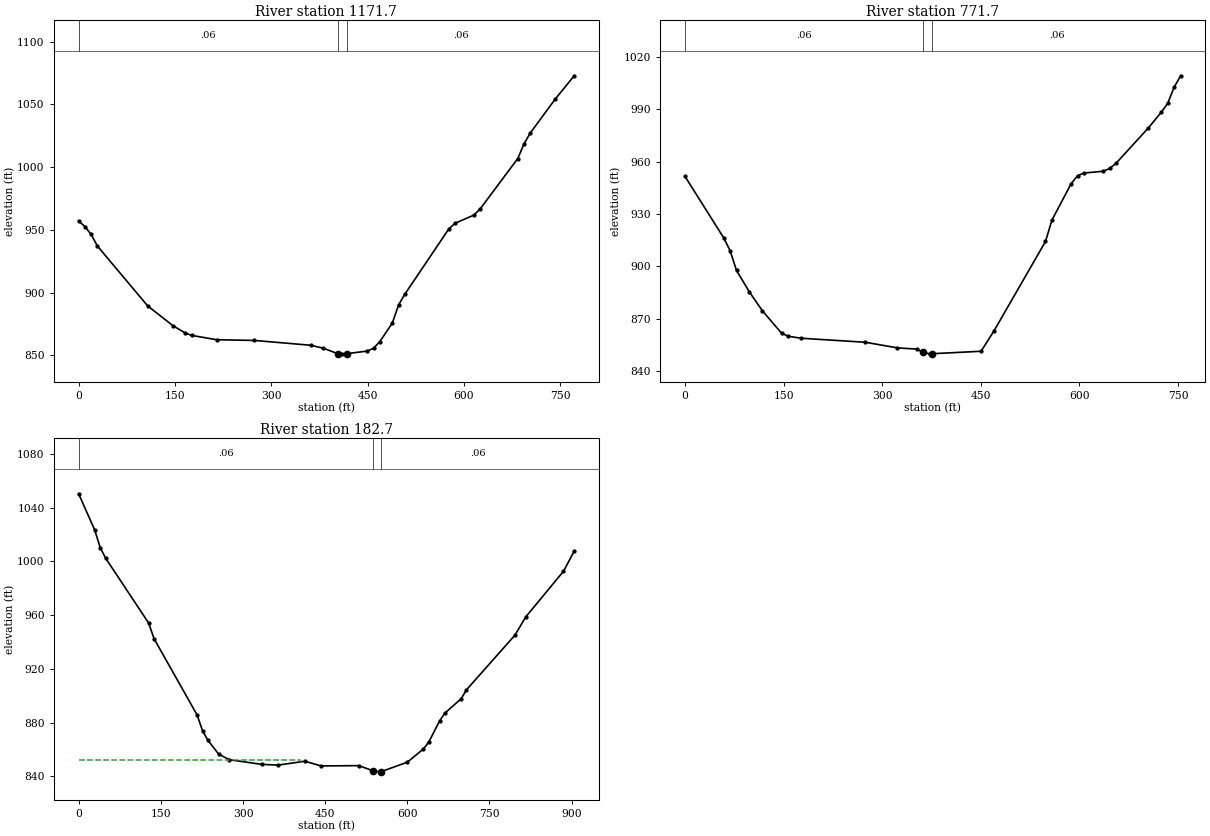
Type RM Length L Ch R = 1 ,1171.7  ,400.3,399.8,399.3
XS GIS Cut Line= 2
     1678489.519       271494.93     1679261.055      271474.173
#Sta/Elev= 30
       0  956.99     9.8  952.62    19.5  946.29    29.3  937.02   107.5  889.39
   146.6  873.71   166.1  867.76   175.9  865.89   214.9  862.42   273.6  861.86
   361.5  858.02     381  855.66   403.4  851.34   410.3  851.18   418.4  851.39
   449.4  853.36   459.2  855.64     469  860.86   488.5  875.73   498.3  890.21
     508  898.73   576.4  950.64   586.2  955.25   615.5  961.72   625.3  966.64
   683.9 1006.83   693.7  1018.6   703.4  1027.2   742.5 1054.39   771.8 1072.75
#Mann= 3 , 0 , 0
       0     .06       0   403.4    .045       0   418.4     .06       0
Bank Sta=403.4,418.4
XS Rating Curve= 0 ,0
Exp/Cntr=0.3,0.1

Type RM Length L Ch R = 1 ,771.7   ,588.1,588.9,589.6
XS GIS Cut Line= 2
     1678479.279      271891.426     1679232.351      271853.772
#Sta/Elev= 30
       0  951.56    58.8  916.37    68.6     909    78.3  897.67    97.9  885.33
   117.5   874.6   146.9  861.67   156.7  859.95   176.3  858.79   274.2  856.48
   323.2  853.24   352.5  852.56   361.4  850.77   372.1  849.83   376.4  849.91
   450.4  851.31     470  862.97   548.4  914.27   558.2  926.57   587.5  947.48
   597.3  952.02   607.1  953.56   636.5  954.57   646.3   956.2   656.1  959.28
     705  979.45   724.6  988.45   734.4  993.56   744.2 1002.82     754 1009.33
#Mann= 3 , 0 , 0
       0     .06       0   361.4    .045       0   376.4     .06       0
Bank Sta=361.4,376.4
XS Rating Curve= 0 ,0
Exp/Cntr=0.3,0.1

Type RM Length L Ch R = 1 ,182.7   ,186.7,182.8,178.9
XS GIS Cut Line= 2
     1678298.043      272463.048      1679202.76      272447.946
#Sta/Elev= 30
       0 1050.33    29.5 1023.26    39.3 1010.32    49.2 1002.46   127.9  954.06
   137.7  942.45   216.4   885.6   226.2  873.87     236  866.88   255.7  856.49
   275.4  852.37   334.4  848.92   363.9  848.36   413.1  851.26   442.6  847.75
   511.4  847.98   537.6  844.14   550.8  843.36   552.6  843.54     600  850.53
   629.5  860.41   639.3   865.5     659  881.26   668.8  887.14   698.3  897.75
   708.1  904.44   796.7  945.15   816.3  958.68   885.2  992.65   904.8 1007.66
#Mann= 3 , 0 , 0
       0     .06       0   537.6    .045       0   552.6     .06       0
#XS Ineff= 2 , 0
          404.78     852
Permanent Ineff=
       F       F
Bank Sta=537.6,552.6
XS Rating Curve= 0 ,0
Exp/Cntr=0.3,0.1

Chan Stop Cuts=-1
Use User Specified Reach Order=0
Composite Channel Slope=5